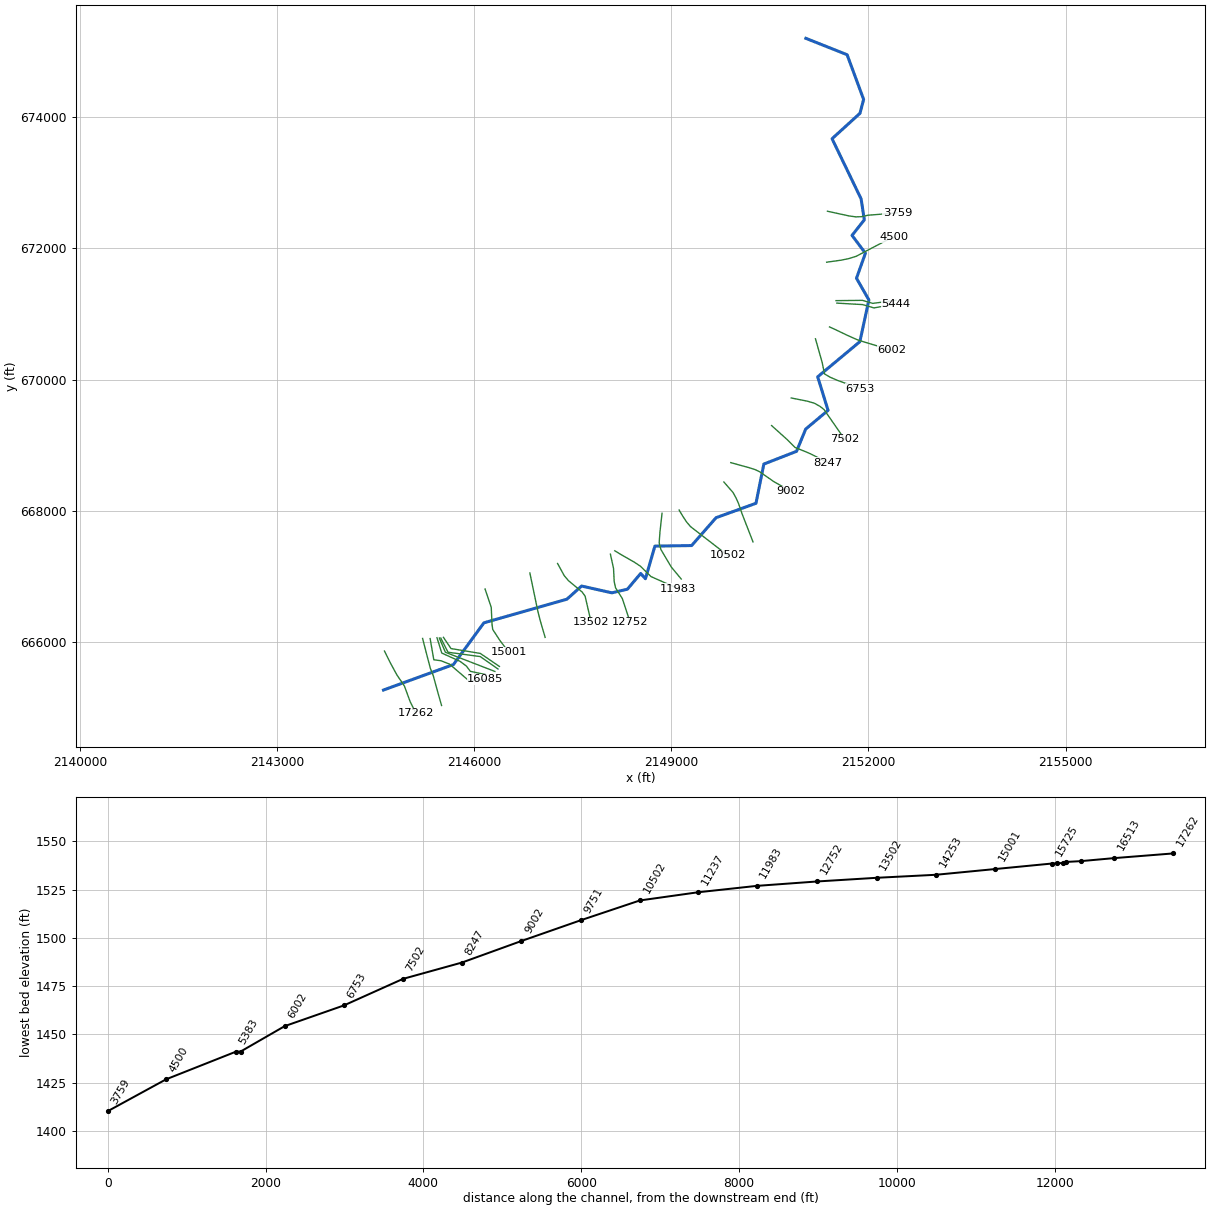
--- WHITECMPFK.prj (project) ---

Proj Title=WHITECMPFK
Current Plan=p01
Default Exp/Contr=0,0
English Units
Geom File=g01
Flow File=f01
Plan File=p01
BEGIN DESCRIPTION:
---------- MODELED AS PART OF WVEMD CTP PROGRAM, 2023----------
Stream Name: Whites Camp Fork
Flood Zone:  AFH
Upshur County, WV
HEC-RAS Version: RAS 6.3
Vertical Datum: NAVD88
Projection: NAD 1983 StatePlane West Virginia S FIPS 4702 (US Feet)
Terrain: 1-meter LIDAR (FEMA Region III 3DEP collected 2016-2018)
Land Use: 2019 NLCD
Hydrologic Method:
WV SIR2010-5033 regression equations
Additional Model Notes:
KWSE at DS boundark with WFORKRV; leveraged XS
END DESCRIPTION:
DSS Export Rating Curves= 0
DSS Export Rating Curve Sorted= 0
DSS Export Volume Flow Curves= 0
DXF OffsetX= 0
DXF OffsetY= 0
DXF ScaleX= 0
DXF ScaleY= 0

--- WHITECMPFK.p01 (plan) ---

Plan Title=Floodplain
Program Version=6.30
Geom File=g01
Flow File=f01
Subcritical Flow
K Sum by GR= 0
Std Step Tol= 0.01
Critical Tol= 0.01
Num of Std Step Trials= 20
Max Error Tol= 0.3
Flow Tol Ratio= 0.001
Split Flow NTrial= 30
Split Flow Tol= 0.02
Split Flow Ratio= 0.02
Log Output Level= 0
Friction Slope Method= 1
Unsteady Friction Slope Method= 2
Unsteady Bridges Friction Slope Method= 1
Parabolic Critical Depth
Global Vel Dist= 0 , 0 , 0
Global Log Level= 0
CheckData=True
Encroach Param=-1 ,0,0, 0
Mapping Interval=1HOUR
Computation Time Step Use Courant=        0
Computation Time Step Use Time Series=    0
Computation Time Step Count To Double=0
Computation Time Step Max Doubling=0
Computation Time Step Max Halving=0
Computation Time Step Residence Courant=0
Run HTab= 0
Run UNet= 0
Run Sediment= 0
Run PostProcess= 0
Run WQNet= 0
Run RASMapper= 0
UNET Theta= 0
UNET Theta Warmup= 0
UNET ZTol= 0
UNET ZSATol= 0
UNET MxIter= 0
UNET Max Iter WO Improvement= 0
UNET MaxInSteps= 0
UNET DtIC= 0
UNET DtMin= 0
UNET MaxCRTS= 0
UNET WFStab= 0
UNET SFStab= 0
UNET WFX= 1
UNET SFX= 1
UNET Gravity=32.17405
UNET 1D Methodology=Finite Difference
UNET DSS MLevel= 1
UNET Pardiso=0
UNET DZMax Abort= 0
UNET Use Existing IB Tables= 0
UNET Froude Reduction=False
UNET Froude Limit= 0
UNET Froude Power= 0
UNET D1 Cores= 0
UNET WindReference=Eulerian
UNET WindDragFormulation=Hsu (1988)
UNET D2 Coriolis=0
UNET D2 Cores= 0
UNET D2 Theta= 1
UNET D2 Theta Warmup= 1
UNET D2 Z Tol= 0.01
UNET D2 Volume Tol= 0.01
UNET D2 Max Iterations= 20
UNET D2 Equation= 0
UNET D2 RampUpFraction=0.1
UNET D2 TimeSlices= 1
UNET D2 Turbulence Formulation=Non-Conservative (original)
UNET D2 Eddy Viscosity=0.3
UNET D2 Transverse Eddy Viscosity=0.1
UNET D2 Smagorinsky Mixing=0
UNET D2 BCVolumeCheck=0
UNET D2 Cores=0
UNET D2 SolverType=PARDISO (Direct)
UNET D2 Minimum Iterations= 3
UNET D2 Maximum Iterations= 30
UNET D2 Restart Number= 10
UNET D2 Relaxation Coeff=1.3
UNET D2 SOR Precondition Iterations= 10
UNET D2 ILUT Maximum Fill= 8
UNET D2 ILUT Tolerance=1E-08
UNET D2 Convergence Tolerance=0.00001
UNET D1D2 MaxIter= 0
UNET D1D2 ZTol=0.01
UNET D1D2 QTol=0.1
UNET D1D2 MinQTol=1
Write IC File= 0
Write IC File at Fixed DateTime=0
Write IC File at Sim End=0
Echo Input=False
Echo Parameters=False
Echo Output=False
Write Detailed= 0
HDF Write Warmup=0
HDF Write Time Slices=0
HDF Flush=0
HDF Compression= 1
HDF Chunk Size= 1
HDF Spatial Parts= 1
HDF Use Max Rows=0
HDF Fixed Rows= 1
Calibration Method= 0
Calibration Iterations= 20
Calibration Max Change=0.05
Calibration Tolerance=0.2
Calibration Maximum=1.5
Calibration Minimum=0.5
Calibration Optimization Method= 1
WQ AD Non Conservative
WQ ULTIMATE=-1
WQ Max Comp Step=1HOUR
WQ Output Interval=15MIN
WQ Output Selected Increments= 0
WQ Output face flow=0
WQ Output face velocity=0
WQ Output face area=0
WQ Output face dispersion=0
WQ Output cell volume=0
WQ Output cell surface area=0
WQ Output cell continuity=0
WQ Output cumulative cell continuity=0
WQ Output face conc=0
WQ Output face dconc_dx=0
WQ Output face courant=0
WQ Output face peclet=0
WQ Output face adv mass=0
WQ Output face disp mass=0
WQ Output cell mass=0
WQ Output cell source sink temp=0
WQ Output nsm pathways=0
WQ Output nsm derived pathways=0
WQ Create Restart=0
WQ Fixed Restart=0
WQ System Summary=0
WQ Write To DSS=0
Sorting and Armoring Iterations= 10
XS Update Threshold= 0.02
Bed Roughness Predictor= 0
Hydraulics Update Threshold= 0.02
Energy Slope Method= 1
Volume Change Method= 1
Sediment Retention Method= 0
Sediment TS Multiplier= 1
Warm Up Method= 0
XS Weighting Method= 0
Number of US Weighted Cross Sections= 1
Number of DS Weighted Cross Sections= 1
Upstream XS Weight=0
Main XS Weight=1
Downstream XS Weight=0
Number of DS XS's Weighted with US Boundary= 1
Upstream Boundary Weight= 1
Weight of XSs Associated with US Boundary= 0
Number of US XS's Weighted with DS Boundary= 1
Downstream Boundary Weight= 0.5
Weight of XSs Associated with DS Boundary= 0.5
Percentile Method= 0
Sediment Output Level= 3
Mass or Volume Output= 0
Output Increment Type= 1
Profile and TS Output Increment= 1
Transport Output Increment 1
XS Output Flag= 0
XS Output Increment= 10
Read HDF5 Sediment Hotstart= 0
Sediment Hotstart Type= 0
Write Gradation File= 0
Read Gradation Hotstart= 0
Write HDF5 File= 1
Write Binary Output= 1
Write DSS Sediment File= 0
DSS Sediment Output Type= 1
SV Curve= 0
Specific Gage Flag= 0
Subcell Erosion Methods= 0
Subcell Deposition Methods= 0
Advection Scheme= 1
Matrix Solver= 0
Implicit Weighting Factor= 1
Maximum Outer Loop Convergence Iterations= 5
Convergence Maximum Absolute= 0.001
Convergence RMSE= 0.0001
Grain Fractions Max Abs Error= 0.001
Max Subgrid Regions= 1
Max Subgrid Length Scale= 3.402823E+38
Initial Layer Thickness= 3.402823E+38
Min Layer Thickness= 3.402823E+38
Max Layer Thickness= 3.402823E+38
Number of Layers= 5

--- WHITECMPFK.f01 (steady flow) ---

Flow Title=Flows
Program Version=6.30
Number of Profiles= 1
Profile Names=01pct
River Rch & RM=WHITECMPFK,Main            ,17262
     721
River Rch & RM=WHITECMPFK,Main            ,14253
     878
River Rch & RM=WHITECMPFK,Main            ,11237
     994
River Rch & RM=WHITECMPFK,Main            ,9002
    1110
River Rch & RM=WHITECMPFK,Main            ,7502
    1250
River Rch & RM=WHITECMPFK,Main            ,5383
    1390
River Rch & RM=WHITECMPFK,Main            ,0
    2060
Boundary for River Rch & Prof#=WHITECMPFK,Main            , 1
Up Type= 0
Dn Type= 1
Dn Known WS=1299.2
DSS Import GetInterval= 0
DSS Import GetPeak= 0
DSS Import FillOption= 0

--- WHITECMPFK.g01 (geometry) ---

Geom Title=Geometry
Program Version=6.30

River Reach=WHITECMPFK      ,Main
Reach XY= 30
     2144617.667665271.4899999952145682.82600003665659.757000014
2146146.35500005666295.2130000142147409.91100003      666654.978
2147633.00500001666855.5209999982148094.55800001666751.844000012
2148331.21600004666807.6180000162148532.50399999667046.792999998
2148605.07499999666966.7250000092148749.21500002667463.562000006
2149308.29400003667472.0330000072149680.10700004667896.241999999
     2150288.005668116.0450000022150407.62100004668713.239999995
2150905.48900001668907.4310000092151044.96500003669246.850000009
     2151385.214669531.7549999952151227.30900002670042.099000022
2151869.23200001670577.6550000162152006.90499999671212.882000014
2151817.92200002671543.6010000112151953.87900002671924.714000016
2151749.98700002672196.2549999952151936.93800002 672433.14200002
2151888.74800001672751.499000013     2151446.024673668.883000001
2151870.80600001674055.5760000052151926.52200001 674267.93900001
2151675.06900005674948.3789999932151047.59157684675198.062639669

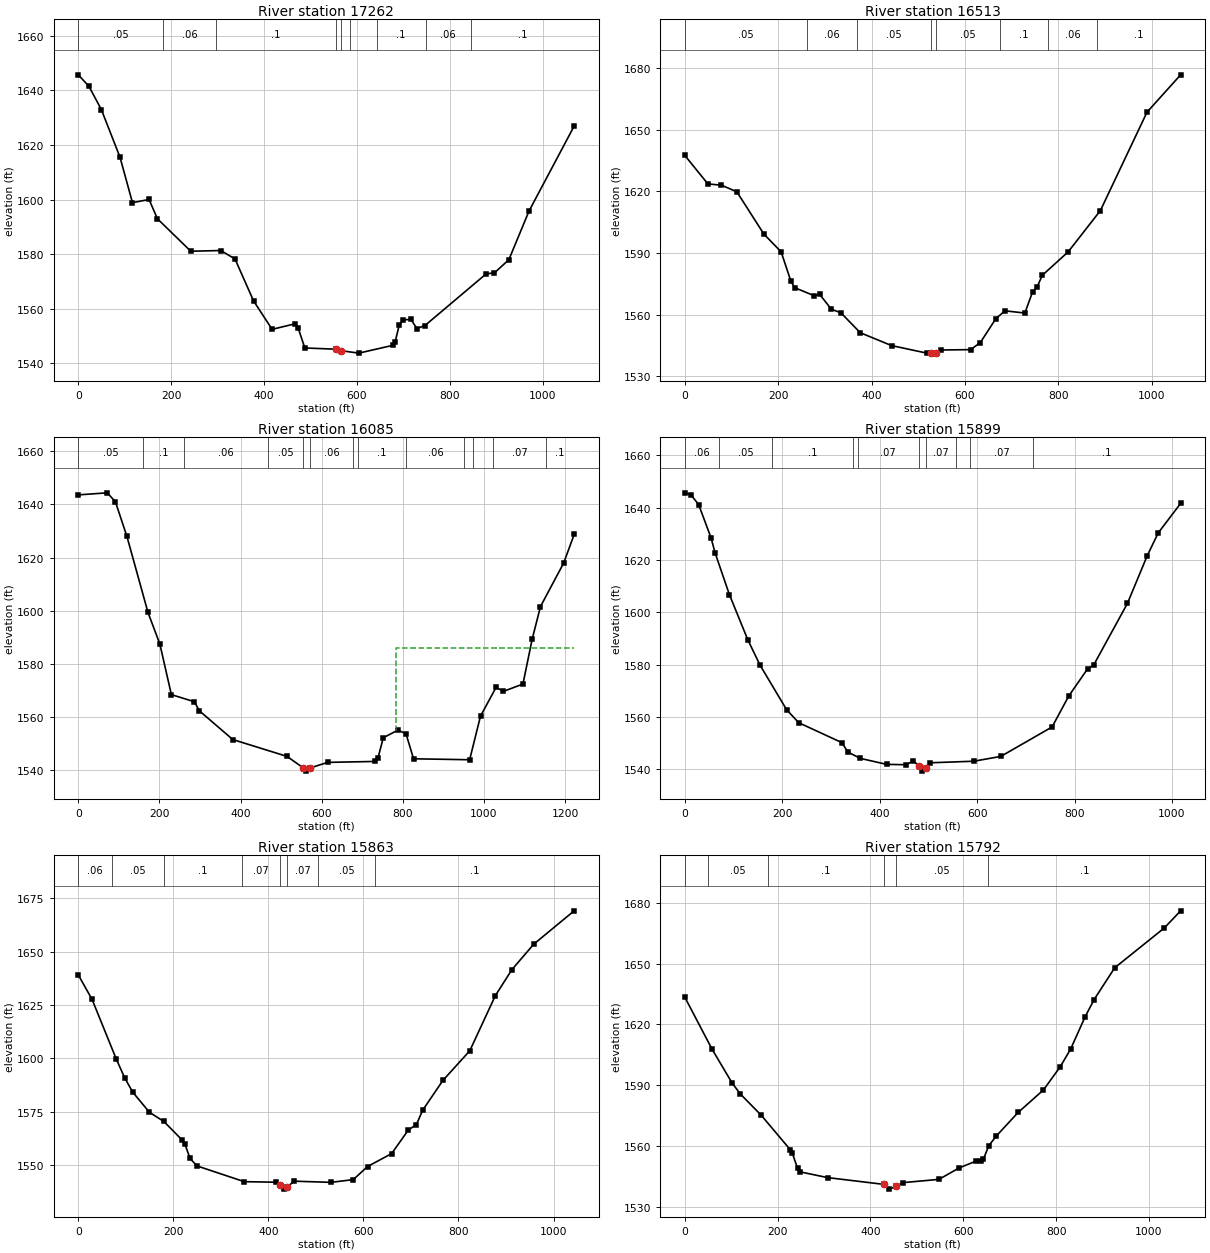
Type RM Length L Ch R = 1 ,17262   ,748.8,748.8,748.8
XS GIS Cut Line= 6
  2144632.306775665865.7021226732144723.90600125665681.493501589
2144822.00521451665501.0850697612144935.16246851665334.551610172
2145024.12423284665093.2538644222145113.02070859664915.807697013
#Sta/Elev= 30
       0  1645.7    22.9 1641.46    49.6 1632.97    89.8 1615.48   116.6 1598.85
   152.4 1600.01   170.3 1592.95   242.2 1581.04   306.9  1581.3   337.5 1578.21
   377.4 1562.87   417.4 1552.41   467.4 1554.46   473.2 1553.08   487.9 1545.58
   554.81545.131   565.51544.582   604.4 1543.69   678.2 1546.58   682.5 1547.82
     691 1553.82   699.5 1555.92   716.5 1556.03   729.3 1552.71   746.4 1553.76
   878.7 1572.77   896.4 1573.11   927.5 1577.95   970.8 1595.74  1068.1 1626.92
#Mann= 9 ,-1,0
       0     .05       0  182.58     .06       0  295.73      .1       0
   554.8    .045       0   565.5      .1       0  584.82     .05       0
  642.46      .1       0  747.89     .06       0  845.69      .1       0
Bank Sta=554.8,565.5
XS Rating Curve= 0 ,0
Exp/Cntr(USF)=0,0
Exp/Cntr=0.3,0.1

Type RM Length L Ch R = 1 ,16513   ,428.6,428.6,428.6
XS GIS Cut Line= 6
2145213.08678143666057.1134852622145287.56858784665766.883750752
2145332.22663501665598.4821846782145375.09170675665490.846901253
2145447.56859593665226.4520888332145501.70004934665035.985278174
#Sta/Elev= 30
       0 1637.41    49.5 1623.54    78.4 1622.94   111.4 1619.73   169.2 1599.22
   206.4 1590.47     227 1576.38   235.3 1573.09   276.6 1569.22     289 1569.82
   313.8 1562.62   334.3 1560.88   375.8 1551.18   442.7 1544.94   518.3 1541.26
   526.61541.544     5381541.394   548.7 1542.78   612.2 1542.96   632.9 1546.38
     666 1557.97   685.6 1561.83   728.3 1560.76     745 1571.14   754.8 1573.58
   765.6  1579.1     821  1590.5   890.1  1610.6   989.9 1658.44  1061.9  1676.6
#Mann= 8 ,-1,0
       0     .05       0  261.06     .06       0  369.63     .05       0
   526.6    .045       0     538     .05       0  674.28      .1       0
  777.15     .06       0  883.86      .1       0
Bank Sta=526.6,538
XS Rating Curve= 0 ,0
Exp/Cntr(USF)=0,0
Exp/Cntr=0.3,0.1

Type RM Length L Ch R = 1 ,16085   ,186,186,186
XS GIS Cut Line= 6
  2145327.798029 666055.245539552145383.57855687665732.305641346
2145492.20379535665717.6265550642145623.50508861665665.958296558
 2145922.0032311665408.9182294142146169.83039261665434.714365184
#Sta/Elev= 30
       0 1643.56    71.3 1644.33    91.4 1640.97   119.8 1627.94   171.7 1599.36
     201 1587.46   229.4 1568.45   286.2 1565.77   298.4 1562.36   380.9 1551.55
   514.7 1545.21  555.11 1540.84     561 1539.68   570.3 1540.82   614.8 1542.97
   731.5 1543.32   739.1 1544.79   751.9 1552.23   787.6 1555.07   807.8 1553.79
   826.5 1544.32   964.8 1543.96   991.6 1560.38  1030.2 1571.23  1047.9 1569.66
  1096.2 1572.43  1119.1 1589.36  1139.5 1601.58  1196.7 1617.95  1222.5 1628.66
#Mann= 13 ,-1,0
       0     .05       0     160      .1       0     260     .06       0
  467.33     .05       0  555.11    .045       0   570.3     .06       0
  678.37     .05       0  688.37      .1       0  808.37     .06       0
  952.12     .07       0  972.12      .1       0 1023.35     .07       0
 1153.35      .1       0
#XS Ineff= 2 , 0
                          782.03         1586.14
Permanent Ineff=
       F       F
Bank Sta=555.11,570.3
XS Rating Curve= 0 ,0
Exp/Cntr(USF)=0,0
Exp/Cntr=0.3,0.1

Type RM Length L Ch R = 1 ,15899   ,33.1,35.6,38
XS GIS Cut Line= 6
2145431.87665145666068.5622726952145504.65860595665834.554469632
 2145786.5735183665706.4950813412145880.54515575665635.555707971
 2145939.5077518665556.3247195332146179.04329824665505.653738554
#Sta/Elev= 30
       0  1645.7    12.5 1644.97    28.5 1641.17    53.8 1628.52    62.2 1622.73
    91.5  1606.8   129.2 1589.56   154.3 1579.85   208.8 1562.81   233.9 1557.78
   322.3 1550.18     335 1546.54   360.4 1544.14   414.5 1541.85   454.4 1541.72
   468.9 1543.18   480.4 1541.39   487.4 1539.27   495.31540.582   503.5 1542.46
   593.5 1543.06   648.7  1544.9     754 1556.17   788.1 1567.98   826.8 1578.38
     839 1579.73   908.6 1603.41   949.4 1621.72   971.9  1630.4  1017.8 1641.65
#Mann= 10 ,-1,0
       0     .06       0      70     .05       0     180      .1       0
  345.07     .06       0  355.07     .07       0   480.4    .045       0
   495.3     .07       0  556.25     .06       0  586.44     .07       0
  714.18      .1       0
Bank Sta=480.4,495.3
XS Rating Curve= 0 ,0
Exp/Cntr(USF)=0,0
Exp/Cntr=0.3,0.1

Type RM Length L Ch R = 1 ,15863   ,62.1,71.3,79.9
XS GIS Cut Line= 3
2145467.87043615666062.7950329912145559.90736342665846.383879685
 2146313.6151732 665554.51902925
#Sta/Elev= 30
       0  1639.1    28.9 1627.67      80 1599.61    97.4 1590.97   114.3 1584.24
   149.5 1574.77     180 1570.43   219.1  1561.6   224.1 1559.93   235.2 1553.08
   249.6 1549.61   349.3 1542.21   415.6 1541.97   424.31540.651   432.8 1538.72
   439.5 1539.71   454.2 1542.45   531.4 1541.89   578.6 1543.18   608.6 1549.31
   659.4 1555.39   694.4 1566.44   711.6    1569   724.5 1575.69   767.3 1589.71
   823.8 1603.59   877.5  1629.4   912.5 1641.66   958.5 1653.59  1043.4 1669.19
#Mann= 8 ,-1,0
       0     .06       0      70     .05       0     180      .1       0
  345.17     .07       0   424.3    .045       0   439.5     .07       0
  505.17     .05       0  625.17      .1       0
Bank Sta=424.3,439.5
XS Rating Curve= 0 ,0
Exp/Cntr(USF)=0,0
Exp/Cntr=0.3,0.1

Type RM Length L Ch R = 1 ,15792   ,73.2,67.2,59.3
XS GIS Cut Line= 4
2145489.42863533666063.6241944982145599.70711575665847.213041192
2146090.57072784665780.880120639 2146360.8773791665591.831297061
#Sta/Elev= 30
       0  1633.4    58.9 1607.62   101.5 1591.16   119.5 1585.61   164.6  1575.1
   227.2 1558.06   231.7 1556.33   242.9 1548.85   248.7 1547.11   307.9 1544.28
   428.41540.958   440.7  1538.6   455.91540.061   469.4  1541.8   547.4 1543.41
   591.1 1549.08   626.8 1552.39   638.9 1552.36     643 1553.29   655.1 1560.11
   671.2 1564.87     718 1576.45   772.6 1587.58   808.5 1598.93   831.1 1607.73
   862.2 1623.62   881.7 1632.19   926.1 1647.89    1033 1667.57  1068.1 1676.02
#Mann= 6 ,-1,0
       0     .06       0      50     .05       0     180      .1       0
   428.4    .045       0   455.9     .05       0  652.89      .1       0
Bank Sta=428.4,455.9
XS Rating Curve= 0 ,0
Exp/Cntr(USF)=0,0
Exp/Cntr=0.3,0.1

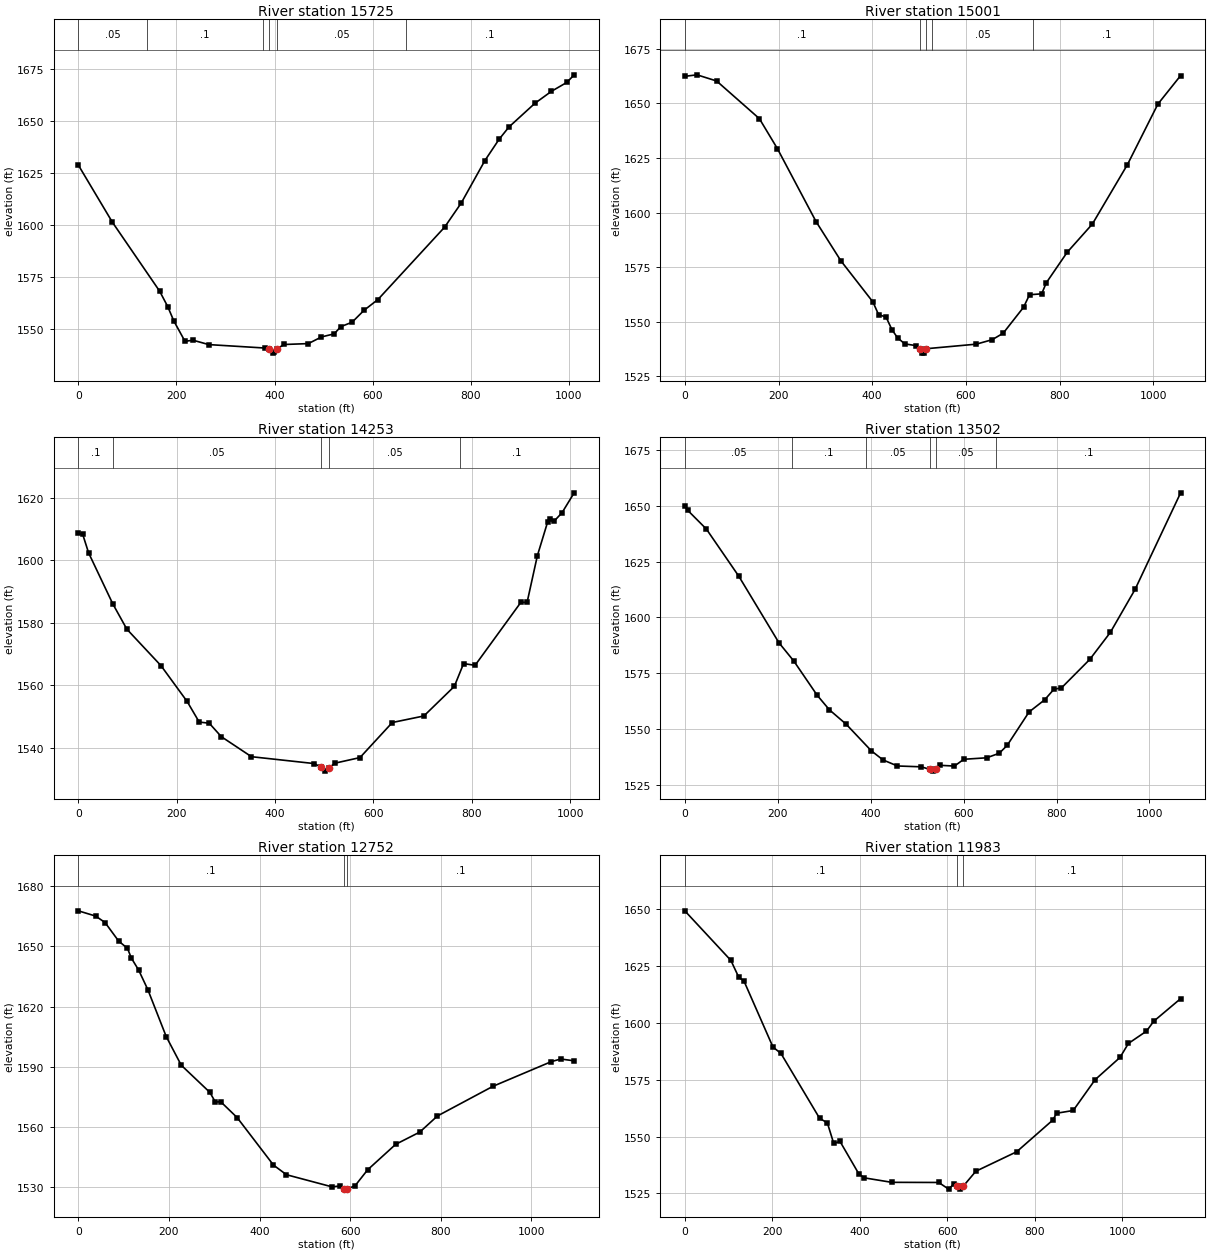
Type RM Length L Ch R = 1 ,15725   ,737.4,723.5,703.3
XS GIS Cut Line= 4
2145530.05754917666074.4032940882145646.14016014665902.766862156
2146091.39988935 665828.971488042146382.43557828665630.801887886
#Sta/Elev= 30
       0 1628.91    69.1 1601.54   165.7 1568.27   182.3  1560.8   194.6 1553.95
   217.4 1544.13   233.6 1544.68     266 1542.56   379.6 1540.92   389.3 1540.29
   395.8 1538.46   399.8 1538.84   404.5 1540.61   420.1 1542.62   468.8 1543.04
   495.6 1546.25   521.5 1547.73   534.9 1551.19     558 1553.33   582.3 1559.05
   610.7 1564.25   746.6 1599.06   780.5 1610.69   828.7  1631.1   857.6 1641.32
   877.7 1647.23   930.5  1658.6   964.3 1664.39   995.8 1668.69  1010.6 1672.32
#Mann= 6 ,-1,0
       0     .05       0     140      .1       0  377.21     .05       0
   389.3    .045       0   404.5     .05       0  668.54      .1       0
Bank Sta=389.3,404.5
XS Rating Curve= 0 ,0
Exp/Cntr(USF)=0,0
Exp/Cntr=0.3,0.1

Type RM Length L Ch R = 1 ,15001   ,741.6,748.5,746.8
XS GIS Cut Line= 6
2146163.81421067666810.3944590092146257.96690951666530.804138929
2146270.22049393666268.3788107482146280.74114217666193.543658584
  2146393.551284666020.5666423442146526.03166209665847.860622928
#Sta/Elev= 30
       0 1662.39      26 1663.08    67.9 1660.26   159.2    1643   197.7 1629.25
   280.3  1595.8   333.1 1577.89   401.5 1559.04   413.5 1553.28   429.6 1552.08
   442.2 1546.31     454 1542.65   469.5 1539.82   493.6 1539.03   501.11537.574
   505.6 1535.62   509.6 1535.59   514.81537.598   622.2  1539.7   656.2 1541.75
   679.6 1544.72     723 1556.59   735.8 1562.34   761.7 1562.75   771.5 1567.78
   816.2  1581.8   869.9 1594.72   944.9    1622  1009.8 1649.69  1058.3 1662.73
#Mann= 5 ,-1,0
       0      .1       0   501.1    .045       0   514.8      .1       0
  528.41     .05       0  742.19      .1       0
Bank Sta=501.1,514.8
XS Rating Curve= 0 ,0
Exp/Cntr(USF)=0,0
Exp/Cntr=0.3,0.1

Type RM Length L Ch R = 1 ,14253   ,741.7,750.9,758.3
XS GIS Cut Line= 6
2146846.01396176667053.6541430952146958.69451067666513.351746008
2146975.60294142666439.3528782582146997.38275351666353.464598596
2147022.94471025666262.243652418 2147078.7054255666073.510434091
#Sta/Elev= 30
       0  1608.6     8.7 1608.41    20.9 1602.38      70 1586.11    98.6 1578.01
   168.1 1566.33   221.2 1554.89   245.7 1548.32   266.2 1547.94   290.7 1543.64
     352 1537.24   478.7 1535.06   494.2 1533.91   502.3 1532.63   509.1 1533.73
   522.7 1535.21   572.6 1536.96   638.3 1548.17   702.5 1550.26   764.4 1559.72
   783.2    1567   806.6 1566.45   899.8 1586.61   912.3 1586.55   933.2 1601.48
     954 1612.23     958 1613.13   966.6 1612.42   983.3 1615.21    1008 1621.58
#Mann= 5 ,-1,0
       0      .1       0      70     .05       0   494.2    .045       0
   509.1     .05       0  776.44      .1       0
Bank Sta=494.2,509.1
XS Rating Curve= 0 ,0
Exp/Cntr(USF)=0,0
Exp/Cntr=0.3,0.1

Type RM Length L Ch R = 1 ,13502   ,750.2,750.1,735.3
XS GIS Cut Line= 6
2147267.64500825667198.8562805062147368.67925501667014.163408428
2147432.36285467666938.0641511682147641.83914176666764.045798421
2147686.81739825666701.213903084  2147778.339853666305.351833925
#Sta/Elev= 30
       0 1650.09     6.3 1648.03    46.4 1639.65   116.2 1618.49   202.5 1588.68
   234.8 1580.39   284.8 1565.12   311.2 1558.57   347.3 1552.11   401.5 1540.17
   426.6 1536.09   457.7 1533.38   509.1    1533   527.1 1531.87   534.6 1531.07
   541.4  1531.9   549.8 1533.67   580.4 1533.34   600.4 1536.38   649.8 1537.05
   676.8 1539.09   693.9 1542.64   740.9  1557.6   774.4 1563.04   794.4 1567.79
   810.7 1568.41   871.7  1581.2   915.9 1593.31     969 1612.55  1067.1 1655.89
#Mann= 6 ,-1,0
       0     .05       0  230.68      .1       0  389.91     .05       0
   527.1    .045       0   541.4     .05       0  669.62      .1       0
Bank Sta=527.1,541.4
XS Rating Curve= 0 ,0
Exp/Cntr(USF)=0,0
Exp/Cntr=0.3,0.1

Type RM Length L Ch R = 1 ,12752   ,760.3,768.6,764.5
XS GIS Cut Line= 6
2148071.82450226 667342.103369342148119.28667767667124.745536342
2148130.05995008666920.5015222582148150.59763867666827.813059345
2148253.23326017666665.3071507512148372.28289084 666304.89645426
#Sta/Elev= 30
       0 1667.72    38.3  1665.1      59 1661.89      89 1652.67   108.5 1649.03
     117 1644.22   133.2 1638.21   153.4  1628.5     194 1605.14   227.2 1590.87
   290.4 1577.34   302.4 1572.56   314.4 1572.67   350.5 1564.82   430.8 1541.15
   459.5 1536.35   560.3  1530.3   577.4 1530.77   585.91529.386   589.3 1529.18
   593.11529.421   610.4  1530.7   638.6 1538.78   700.5 1551.47   753.8 1557.58
   792.8  1565.6   915.2 1580.35  1044.4 1592.67  1065.1 1593.95  1094.6 1593.05
#Mann= 3 ,-1,0
       0      .1       0   585.9    .045       0   593.1      .1       0
Bank Sta=585.9,593.1
XS Rating Curve= 0 ,0
Exp/Cntr(USF)=0,0
Exp/Cntr=0.3,0.1

Type RM Length L Ch R = 1 ,11983   ,747.9,746.3,727
XS GIS Cut Line= 6
2148138.21478942667392.6062210952148234.40751043667334.079763338
2148434.52325192667219.9267764242148530.13329692667156.643110335
2148689.70909326666999.6047105042149102.29947542666815.775681838
#Sta/Elev= 30
       0 1649.34   105.3 1627.53   123.4 1620.09   135.2 1618.47   201.5 1589.41
   219.8 1586.58   308.2 1558.03   325.8 1556.05   340.4    1547   354.8 1547.86
   397.7 1533.63   409.7 1531.87   472.9 1529.88   580.4 1529.82     603 1526.89
   615.5 1529.25  622.38 1528.17   629.8    1527   636.31528.139   665.2 1534.75
   758.6 1543.33   841.1 1557.27   849.9 1560.28   887.8 1561.49   937.9 1575.05
   994.8 1584.84  1013.9 1590.98  1055.1 1596.38    1072 1600.78  1133.3  1610.7
#Mann= 3 ,-1,0
       0      .1       0  622.38    .045       0   636.3      .1       0
Bank Sta=622.38,636.3
XS Rating Curve= 0 ,0
Exp/Cntr(USF)=0,0
Exp/Cntr=0.3,0.1

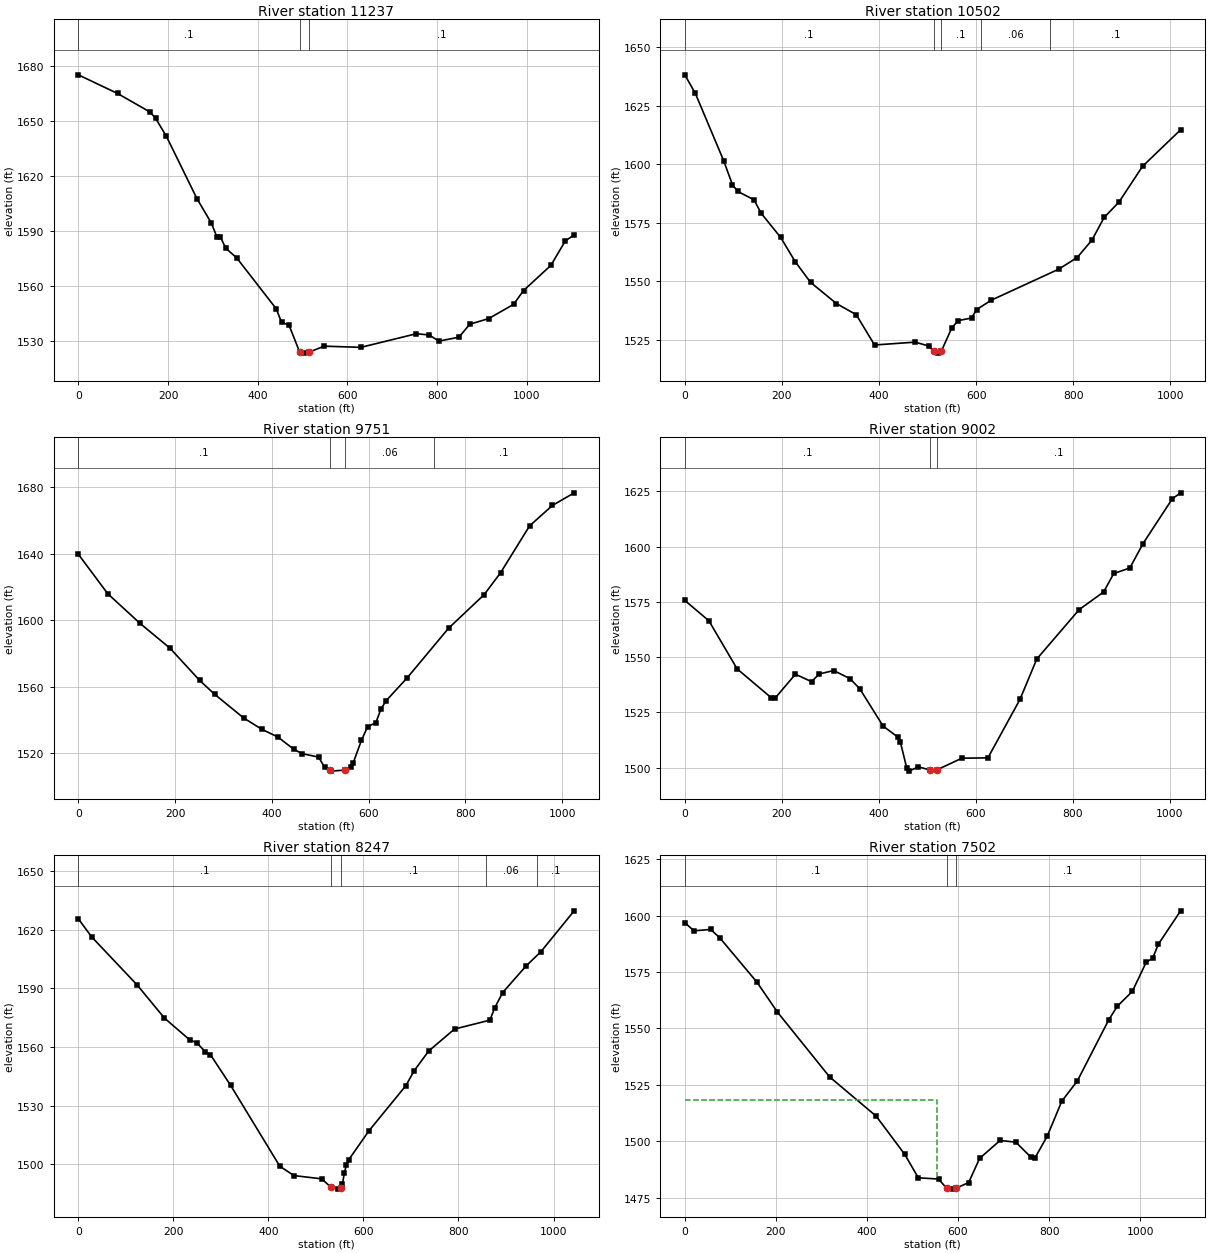
Type RM Length L Ch R = 1 ,11237   ,724.8,734.6,740.8
XS GIS Cut Line= 6
2148857.83539742667964.2067839212148826.24294092667676.698500678
2148814.21671826667514.6059770882148840.50373918667412.219698921
2148997.72422525667145.8449035882149150.20456333 666962.02506125
#Sta/Elev= 30
       0 1675.12    87.4 1664.97     160 1654.84   172.1 1651.54   196.3 1641.67
   264.6 1607.66   296.8 1594.34   308.8 1586.96   316.9 1586.77   328.9 1580.63
     353  1575.5   441.2 1547.75   453.3  1540.3   469.8 1538.85  493.48 1524.19
   502.8 1523.57   515.2 1524.18   548.3 1527.36   630.1 1526.72     754 1534.14
     782 1533.47   804.3 1530.13   848.8 1532.24     873 1539.33   914.7 1542.34
   970.7 1550.12   992.8 1557.67  1053.8 1571.35  1086.1 1584.72  1105.7 1587.94
#Mann= 3 ,-1,0
       0      .1       0  493.48    .045       0   515.2      .1       0
Bank Sta=493.48,515.2
XS Rating Curve= 0 ,0
Exp/Cntr(USF)=0,0
Exp/Cntr=0.3,0.1

Type RM Length L Ch R = 1 ,10502   ,756.3,750.8,734.5
XS GIS Cut Line= 6
2149117.81552051668012.5350993422149172.92499034667920.247226179
2149229.81792118667833.5213497582149291.81910951667760.446036592
2149778.80599642667383.8326165832149856.67460708667323.612920761
#Sta/Elev= 30
       0  1638.1    21.7 1630.19      80 1601.49    98.2 1591.16   109.2 1588.33
   142.6 1584.77   157.2 1579.03   197.3 1568.77   227.2 1558.44   258.9 1549.56
   312.4 1540.48     353 1535.77   390.8 1522.82   474.4 1524.04     502 1522.41
   512.21520.192   520.6 1519.35   528.2 1520.14   550.2 1530.27   563.4 1533.25
   590.7 1534.33   600.8 1537.92   631.1 1541.93   770.1 1555.18   808.1 1560.15
   838.4 1567.57   863.7 1577.26   894.1 1583.79   942.6 1599.04  1021.1 1614.65
#Mann= 5 ,-1,0
       0      .1       0   512.2    .045       0   528.2      .1       0
  609.55     .06       0  752.05      .1       0
Bank Sta=512.2,528.2
XS Rating Curve= 0 ,0
Exp/Cntr(USF)=0,0
Exp/Cntr=0.3,0.1

Type RM Length L Ch R = 1 ,9751    ,745.6,749.3,769.7
XS GIS Cut Line= 6
2149799.48377658 668439.78719759 2149939.0461615668279.653003424
2149984.29902376668196.5550725012150020.81929192668116.753066748
2150078.06458426 667950.999133172150242.83033083667527.240794346
#Sta/Elev= 30
       0 1639.59    60.9  1615.8   127.3 1598.05   189.5 1583.05   250.5 1563.76
   281.7 1555.33   341.6  1541.1     379  1534.3   412.6 1529.58   445.7 1522.14
   462.8 1519.59   496.6 1517.53   509.2 1511.29   519.3 1509.68   521.8 1509.08
  552.13 1509.72   563.8 1511.56     568  1513.9   585.1 1527.53   597.9 1535.76
   615.1 1538.33   625.7 1546.57   636.5 1551.55   679.5 1565.13   765.4  1595.1
   838.8 1615.27   872.8 1628.46   932.9 1656.71     980 1668.96  1024.9 1676.55
#Mann= 4 ,-1,0
       0      .1       0   519.3    .045       0  552.13     .06       0
  734.45      .1       0
Bank Sta=519.3,552.13
XS Rating Curve= 0 ,0
Exp/Cntr(USF)=0,0
Exp/Cntr=0.3,0.1

Type RM Length L Ch R = 1 ,9002    ,748.9,755.1,756.9
XS GIS Cut Line= 6
2149904.43172942 668735.31482175 2150190.9200016668655.937027752
2150276.77153592668628.3104425822150345.20282951668595.448303595
  2150560.452399668445.2031972562150818.87642284 668299.92920959
#Sta/Elev= 30
       0 1575.67    49.7 1566.46   107.9 1544.67   178.4 1531.59   186.7 1531.55
   228.1 1542.25   261.3  1538.9   277.3 1542.37     307 1543.92   340.6 1540.28
   360.9 1535.65     409 1518.75   440.1 1513.68   444.5 1511.63   457.8 1499.65
   462.2 1498.38   481.7 1500.31   505.91498.899   520.6 1499.02   571.6 1504.25
   625.1 1504.38   691.2 1530.86   725.9 1549.15   813.2 1571.49   863.8 1579.53
   884.6 1587.87   917.8 1590.36     945 1601.42  1005.4  1621.7  1022.5 1624.39
#Mann= 3 ,-1,0
       0      .1       0   505.9    .045       0   520.6      .1       0
Bank Sta=505.9,520.6
XS Rating Curve= 0 ,0
Exp/Cntr(USF)=0,0
Exp/Cntr=0.3,0.1

Type RM Length L Ch R = 1 ,8247    ,749.3,745.3,732
XS GIS Cut Line= 6
2150525.48527734669299.7172362512150758.23842075 669090.45617184
2150884.18567543668965.3333905942151046.83069134668900.107143089
2151126.99391684668864.6449436692151386.13939592668734.742316335
#Sta/Elev= 30
       0 1625.69    27.8 1616.46   123.6 1591.82   181.1 1574.84   234.9 1563.55
   249.1 1562.22   267.1 1557.59   277.9 1556.11   320.6  1540.3   424.1  1498.9
   453.9 1494.14     512 1492.48   532.2 1488.07     547 1487.21   552.8    1488
   555.7 1489.81     560 1495.68   564.3 1499.76   568.7 1502.15   611.7 1517.12
   689.2  1540.2   706.7 1547.84   737.3 1557.95   791.6 1569.19     866 1573.76
   876.6 1580.23   892.8 1587.82     942 1601.46   973.5 1608.83  1043.4 1629.75
#Mann= 5 ,-1,0
       0      .1       0   532.2    .045       0   552.8      .1       0
  857.51     .06       0   964.7      .1       0
Bank Sta=532.2,552.8
XS Rating Curve= 0 ,0
Exp/Cntr(USF)=0,0
Exp/Cntr=0.3,0.1

Type RM Length L Ch R = 1 ,7502    ,745.5,748.9,738.6
XS GIS Cut Line= 6
2150824.56243509669719.8121965832151069.80931993669671.332962841
2151177.35930167669639.9445741772151261.26858267669592.751099005
2151323.37672618669544.1783615052151637.66612384669090.918769345
#Sta/Elev= 30
       0 1596.92      20 1593.29    56.7  1593.9    76.8 1590.19   158.6 1570.47
   203.5 1557.23   318.1  1528.5   420.3 1511.12   482.9 1494.19   512.8  1483.8
   557.1 1483.25   574.7 1479.24   589.2 1478.78   595.2 1479.18   623.2 1481.66
   647.4 1492.42   692.3 1500.36   726.8 1499.59   759.5 1493.05   769.3 1492.77
   795.8 1502.26   827.7 1517.73   861.9 1526.74   930.8  1553.8   949.5 1559.81
   982.6 1566.43  1012.9 1579.26  1027.5 1581.24    1040 1587.43  1088.7 1602.15
#Mann= 3 ,-1,0
       0      .1       0   574.7    .045       0   595.2      .1       0
#XS Ineff= 2 , 0
          554.71 1518.21
Permanent Ineff=
       F       F
Bank Sta=574.7,595.2
XS Rating Curve= 0 ,0
Exp/Cntr(USF)=0,0
Exp/Cntr=0.3,0.1

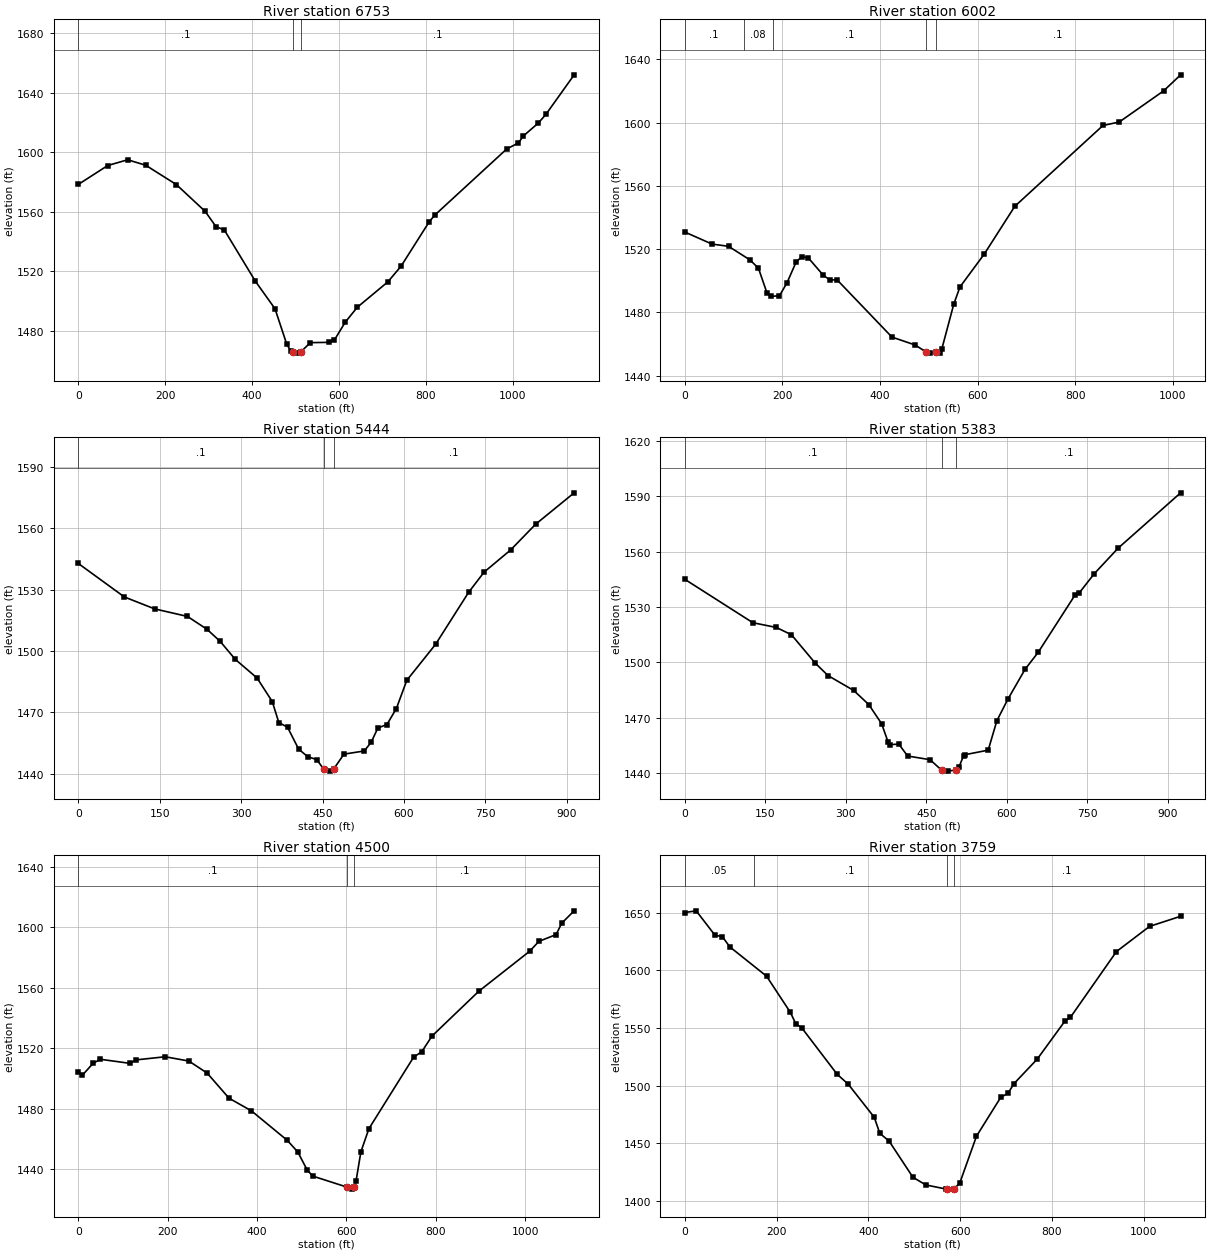
Type RM Length L Ch R = 1 ,6753    ,721.7,750.5,757.5
XS GIS Cut Line= 6
2151193.51707776670621.8937257532151296.02441867670258.338350505
2151331.26680225670086.9239951672151415.25777601670036.750867173
2151527.87270826 669988.243746342151873.94878776669862.510073915
#Sta/Elev= 30
       0 1578.36    67.6 1591.03   113.5  1594.9   155.1 1591.24   225.7 1578.25
     292 1560.25   316.7 1550.08   336.3 1547.66   407.7 1513.27   452.8 1494.84
   479.8 1471.04   489.4 1466.35   495.31465.969   505.7 1465.04  512.44 1465.95
   534.2 1472.08   577.1 1472.28   589.7  1473.9   614.4 1485.79   642.2 1495.83
   712.6 1512.91   743.1 1523.47     808 1553.34   820.9 1557.82   986.7 1602.28
  1013.1 1606.16  1024.2 1610.79    1059 1619.59  1076.4 1625.36  1141.5 1651.96
#Mann= 3 ,-1,0
       0      .1       0   495.3    .045       0  512.44      .1       0
Bank Sta=495.3,512.44
XS Rating Curve= 0 ,0
Exp/Cntr(USF)=0,0
Exp/Cntr=0.3,0.1

Type RM Length L Ch R = 1 ,6002    ,547.7,558,555.2
XS GIS Cut Line= 6
2151407.18430135  670802.06560952151498.69560125670760.733999252
2151672.86388808670676.8676971792151826.36784618670608.292374998
2151924.30990751670576.1907331792152356.63483025670446.341583416
#Sta/Elev= 30
       0 1530.84    55.8 1523.23    89.6 1521.83   133.2 1513.31   150.9 1508.04
   168.7 1492.09     176 1490.19     194 1490.57   209.6 1498.82   228.1 1511.85
   239.7 1515.25     253 1514.58   283.7 1503.58   297.4 1500.54   312.1 1500.65
   424.6 1464.46   472.2 1459.46   494.3 1455.08   501.6 1454.32   514.3 1455.03
   522.7  1454.7   526.9 1457.03   551.4 1485.36     564 1496.13     614 1517.01
   676.4 1547.09   857.1 1598.17   890.6 1600.39   981.6 1620.08  1016.3 1630.19
#Mann= 5 ,-1,0
       0      .1       0  120.41     .08       0  180.41      .1       0
   494.3    .045       0   514.3      .1       0
Bank Sta=494.3,514.3
XS Rating Curve= 0 ,0
Exp/Cntr(USF)=0,0
Exp/Cntr=0.3,0.1

Type RM Length L Ch R = 1 ,5444    ,61.4,61.2,61.1
XS GIS Cut Line= 4
2151519.44881759671164.8554828382151911.21846725671142.388406155
2152083.93411925671091.8374836172152419.53607721671152.217752204
#Sta/Elev= 30
       0 1542.81    84.9 1526.41   140.6 1520.59   201.1 1516.89   237.1 1510.59
   261.2 1504.71   289.2 1495.87   329.3 1486.75   357.3 1475.21   369.3 1464.98
   385.4 1462.67   405.9 1451.92   422.6 1448.27   439.3 1446.82   451.8 1442.22
   464.3 1441.19   470.21442.132   489.3  1449.5   526.8 1451.06   539.4  1455.3
   551.8 1462.29   568.5    1464   585.9 1471.84   605.1 1485.63     658 1503.21
   718.9 1528.66   747.4 1538.57   796.2 1549.39   842.4 1562.02   913.4 1577.39
#Mann= 3 ,-1,0
       0      .1       0   451.8    .045       0   470.2      .1       0
Bank Sta=451.8,470.2
XS Rating Curve= 0 ,0
Exp/Cntr(USF)=0,0
Exp/Cntr=0.3,0.1

Type RM Length L Ch R = 1 ,5383    ,865.1,882.7,890.1
XS GIS Cut Line= 4
2151505.40689466671202.7686747412151908.41008267671206.981251619
2152065.67961945 671160.642905962152419.53607721671208.385443912
#Sta/Elev= 30
       0 1545.06   126.8 1521.53   170.8 1518.94   198.8 1514.98   242.8 1499.72
   266.8 1492.89   314.8  1484.8   342.8 1477.19   366.8 1466.78   378.8 1456.91
   382.8 1455.44   398.8 1455.74   415.3 1449.28     457 1447.29   478.4 1441.67
   490.4 1441.09   505.41441.702   511.2 1443.47   519.5 1449.42   522.6 1450.02
   565.4 1452.46   581.6 1468.44   601.9 1479.98   634.1 1496.27   658.6  1505.5
   726.9 1536.39     735 1537.65   763.2 1548.13   807.6 1561.95     924 1591.92
#Mann= 3 ,-1,0
       0      .1       0   478.4    .045       0   505.4      .1       0
Bank Sta=478.4,505.4
XS Rating Curve= 0 ,0
Exp/Cntr(USF)=0,0
Exp/Cntr=0.3,0.1

Type RM Length L Ch R = 1 ,4500    ,738,741.3,727.7
XS GIS Cut Line= 6
    2151363.4941671788.2181647572151588.22494976671819.719086006
2151702.67419593 671843.721662672151811.91774385671877.388262004
2152300.10574384672134.1308587492152394.46611942672165.937881753
#Sta/Elev= 30
       0 1504.38     8.8 1502.11    32.9 1509.98    49.1 1512.72   115.8 1510.01
   129.7 1512.33   194.5 1514.38   247.3 1511.54   288.2 1503.59   337.2 1486.97
   387.3  1478.6   467.4 1459.12   491.2 1451.35   511.7 1439.68   524.2 1435.47
   601.8  1428.1   612.5 1426.82  617.82 1428.14   621.3 1431.97   632.3 1451.51
   650.2 1466.79   750.3 1514.14   768.5  1517.7   791.3 1528.05   896.1 1557.72
    1010 1584.19  1030.6 1590.71  1069.1 1595.19  1081.7 1602.76  1109.5 1610.91
#Mann= 3 ,-1,0
       0      .1       0   601.8    .045       0  617.82      .1       0
Bank Sta=601.8,617.82
XS Rating Curve= 0 ,0
Exp/Cntr(USF)=0,0
Exp/Cntr=0.3,0.1

Type RM Length L Ch R = 1 ,3759    ,293.3,298.2,297.5
XS GIS Cut Line= 6
  2151375.828721672564.5082788322151699.59939893672493.956254587
2151805.77405535672478.9205235092151891.66528776672481.118681833
  2151993.488903 672503.748885932152443.66648035 672539.08838217
#Sta/Elev= 30
       0  1650.2    24.8 1651.67    65.6 1630.59    81.9 1629.21    98.2 1620.37
   178.2 1594.97   229.8 1563.74   242.1 1553.55   254.3 1550.47     332 1509.89
   356.2 1501.28   412.8 1472.59   424.9 1458.69   445.1    1452   497.1 1420.58
   525.1 1413.93   570.2 1410.29   570.71410.301   585.61410.328   598.9 1415.28
   635.6 1456.21   688.5 1489.94   704.3 1493.42   717.3  1501.8     768 1523.09
   828.2 1555.99   840.2 1559.24   940.5 1616.31  1012.7 1638.17  1080.4 1646.94
#Mann= 4 ,-1,0
       0     .05       0  150.01      .1       0   570.7    .045       0
   585.6      .1       0
Bank Sta=570.7,585.6
XS Rating Curve= 0 ,0
Exp/Cntr(USF)=0,0
Exp/Cntr=0.3,0.1