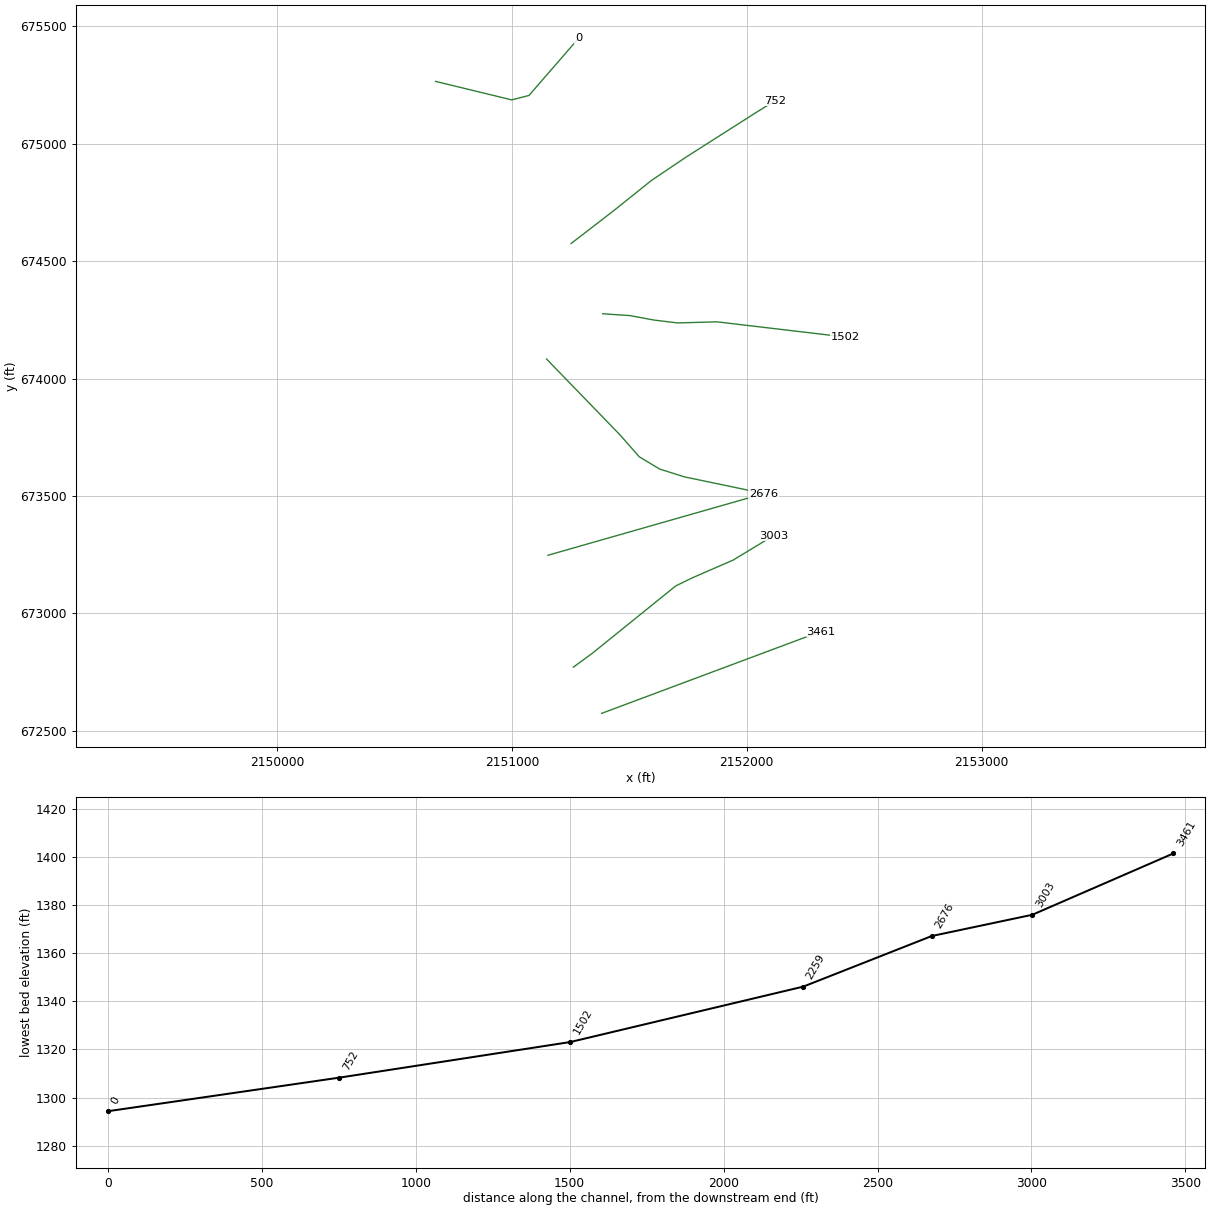
HEC-RAS study WHITECMPFK.prj: WHITECMPFK

--- WHITECMPFK.g01 (geometry) --- (continued)

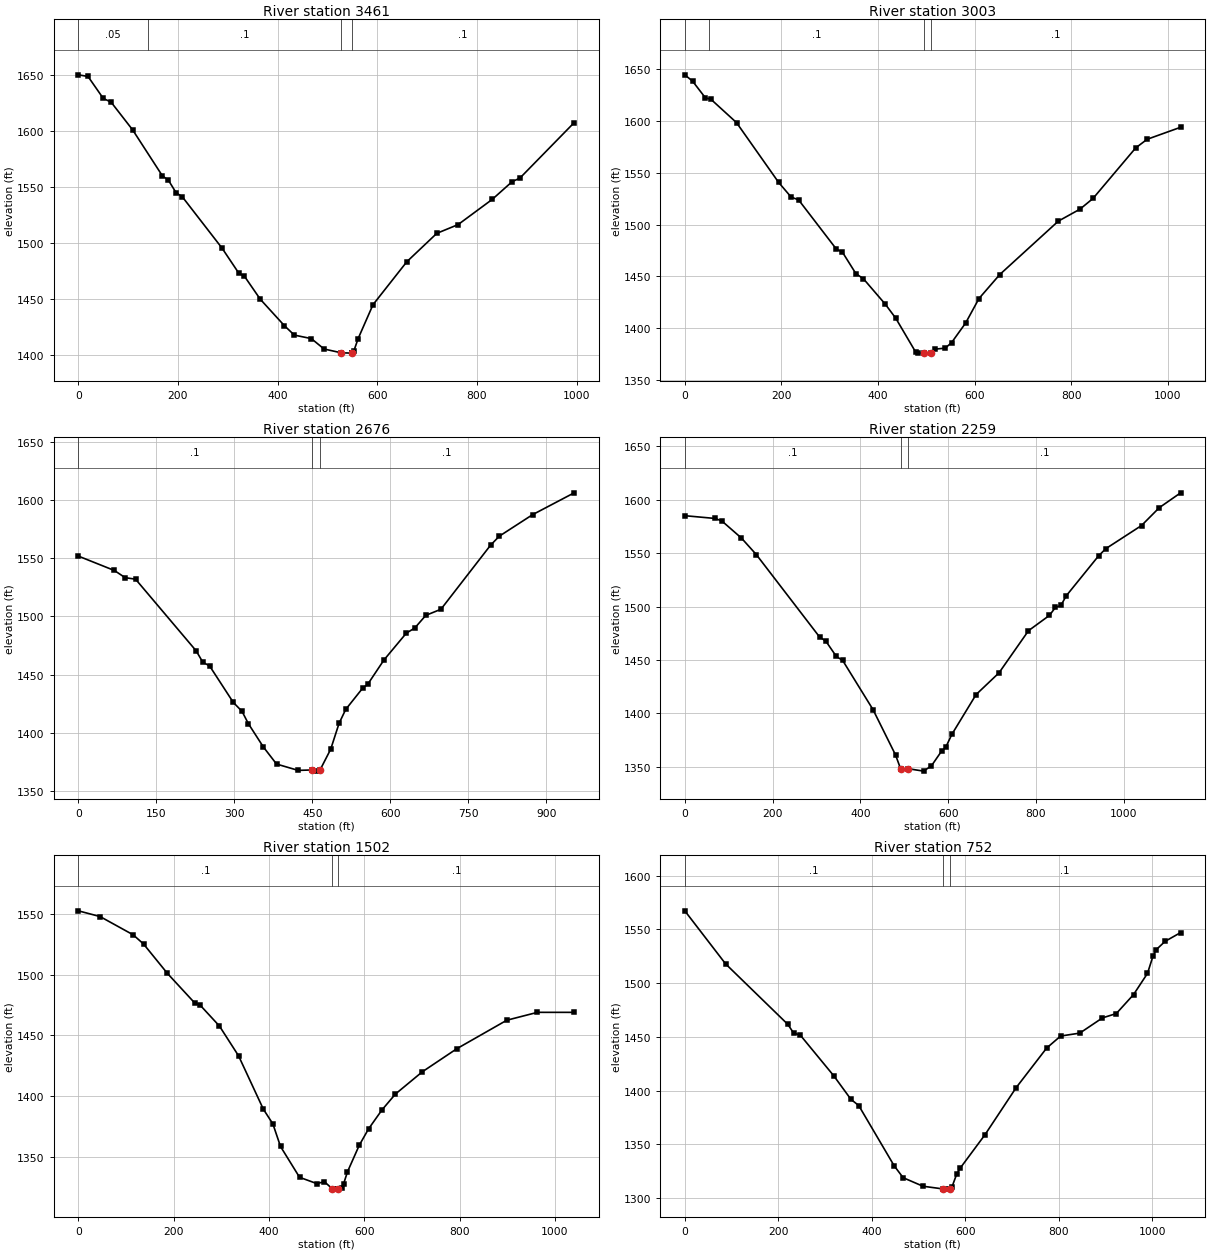
Type RM Length L Ch R = 1 ,3461    ,444.8,458.4,441.6
XS GIS Cut Line= 2
2151382.02519608672574.8334309552152314.37124609672923.081263862
#Sta/Elev= 30
       0 1649.98    19.4 1648.53    50.1  1628.9    65.7 1625.61   109.2 1600.69
   168.8 1559.69   180.7 1555.91   196.2 1544.67   208.7 1541.02   288.4 1495.21
   322.5 1472.53     333 1470.31   365.2 1449.53   413.8  1425.8   433.6 1417.46
   467.7 1414.34   493.3 1405.03   527.5 1401.68   548.8 1401.36  550.03 1401.75
   553.1  1403.4   561.7 1414.37   591.5 1444.63   659.4    1483   719.6 1508.38
   762.3 1516.18   830.7 1538.65   870.8 1554.54   886.2 1557.64   995.3 1607.26
#Mann= 4 ,-1,0
       0     .05       0     140      .1       0   527.5    .045       0
  550.03      .1       0
Bank Sta=527.5,550.03
XS Rating Curve= 0 ,0
Exp/Cntr(USF)=0,0
Exp/Cntr=0.3,0.1

Type RM Length L Ch R = 1 ,3003    ,328.7,326.7,317.9
XS GIS Cut Line= 6
2151262.02612709672771.7034025042151341.59027243672829.826973915
2151697.39238234673117.1794175952151768.91487709673152.029085428
2151940.96833876673226.7517050062152114.66877876673331.811862335
#Sta/Elev= 30
       0 1644.58    16.1 1638.45    42.7 1622.31    54.1 1620.96     107 1598.45
   194.3 1540.63   220.1 1526.53   235.5 1523.84   313.6 1476.34   326.3  1473.3
   354.1 1452.62   369.6 1447.71   415.1 1423.02   436.6 1409.55   477.6 1377.04
   482.7 1375.88   494.61376.047   509.11376.437   518.5 1379.78     539 1380.68
   552.2 1386.11   581.2 1404.97   608.8  1428.6   651.9 1451.79     773 1503.32
   817.8 1514.88   844.8 1525.22   933.1 1574.01   956.8 1582.34  1026.1 1593.95
#Mann= 4 ,-1,0
       0     .05       0      50      .1       0   494.6    .045       0
   509.1      .1       0
Bank Sta=494.6,509.1
XS Rating Curve= 0 ,0
Exp/Cntr(USF)=0,0
Exp/Cntr=0.3,0.1

Type RM Length L Ch R = 1 ,2676    ,431.1,417.1,399.8
XS GIS Cut Line= 2
2151153.51274309673247.7194288172152070.64828589673509.651548853
#Sta/Elev= 30
       0 1551.93    69.3 1539.56    90.1 1533.38   110.1 1532.06   226.6  1470.5
   239.5 1460.66   252.4 1457.56   298.1 1426.12   314.8  1418.5   327.2 1407.78
     356 1387.77   381.3 1373.13   422.9 1367.69   449.61368.058   456.9 1367.05
  465.06 1368.11   485.5 1385.92   501.6 1408.19   514.4 1420.13   546.9 1438.35
   556.7 1441.72   587.9 1462.61   630.9 1485.65   647.3 1490.14   668.4 1500.97
   697.5 1506.21   792.9 1561.25   809.8 1569.04   873.8 1587.54   953.8 1606.32
#Mann= 3 ,-1,0
       0      .1       0   449.6    .045       0  465.06      .1       0
Bank Sta=449.6,465.06
XS Rating Curve= 0 ,0
Exp/Cntr(USF)=0,0
Exp/Cntr=0.3,0.1

Type RM Length L Ch R = 1 ,2259    ,739.9,756.4,758.3
XS GIS Cut Line= 6
2151147.70056833674082.9097695952151462.08609442673758.339880675
2151542.15089493673666.900102928  2151628.702231673614.843120426
2151733.74434376673581.5429901782152071.34078142673511.065440834
#Sta/Elev= 30
       0 1585.15    69.5 1582.54    84.6 1580.14   128.9 1564.27   162.9 1548.75
   307.1 1471.58   321.3 1467.75   345.2 1453.41   359.7 1449.63   428.8 1403.64
   480.1  1361.2   491.5 1348.41   509.51348.284   543.9 1346.05   561.9 1351.02
   584.9 1364.71   594.5 1368.42   608.5 1380.52   663.6 1417.71   715.9 1438.08
     783  1477.5   830.6 1491.79   844.5 1499.32   856.8  1501.1   869.1 1510.19
   942.6 1547.49     959 1554.23  1040.5 1575.94  1081.1 1592.69  1129.6 1606.55
#Mann= 3 ,-1,0
       0      .1       0   491.5    .045       0   509.5      .1       0
Bank Sta=491.5,509.5
XS Rating Curve= 0 ,0
Exp/Cntr(USF)=0,0
Exp/Cntr=0.3,0.1

Type RM Length L Ch R = 1 ,1502    ,739.7,750.3,755.7
XS GIS Cut Line= 6
2151386.66203268 674275.48648417  2151501.600123674267.884137169
2151606.34072718674248.5213150082151705.84118435674236.501653999
2151872.80049609 674241.187340172152420.59303567 674176.46306017
#Sta/Elev= 30
       0 1553.02    45.6 1548.29   115.2 1533.17   136.9 1525.59     187  1501.3
   244.3 1476.85   255.8 1475.01   296.1 1457.83   336.3 1433.18   388.3 1389.11
   408.3 1376.95   424.3  1358.3   464.3 1332.82   500.4 1327.63   516.5 1329.16
   533.41323.175   540.7 1323.05     546 1323.34   552.7 1324.39   556.8  1327.5
   564.8  1337.3   589.6 1359.32   609.1 1372.83   637.3 1388.53   665.5 1401.62
   721.9 1419.99   794.4 1439.09   899.2 1462.62   963.6 1469.14  1040.6 1469.12
#Mann= 3 ,-1,0
       0      .1       0   533.4    .045       0     546      .1       0
Bank Sta=533.4,546
XS Rating Curve= 0 ,0
Exp/Cntr(USF)=0,0
Exp/Cntr=0.3,0.1

Type RM Length L Ch R = 1 ,752     ,752.1,752.1,752.1
XS GIS Cut Line= 6
2151252.32142209    674574.60334 2151430.4293336674711.789417341
2151594.00315343674842.7543785132151739.11441176674940.569471583
2152036.98061392675130.4496692572152120.68681134675182.389854088
#Sta/Elev= 30
       0 1567.25    87.3 1517.89   220.6 1461.54   232.7  1453.6   247.5  1451.4
   318.9 1413.67   355.6 1391.78   372.2 1386.07   448.2 1329.89   467.3 1318.89
   509.7 1310.96   552.3 1308.46   555.8 1308.26   566.91308.565   572.1 1310.67
   581.8 1322.15     589 1327.58   642.4 1358.87     709 1402.63   774.3  1439.5
   804.3 1450.73   845.3 1453.44   893.8 1467.61   923.4 1471.64   960.3 1489.28
   990.2 1509.05  1001.8 1524.89  1008.7 1531.03  1027.9 1538.86  1061.1    1547
#Mann= 3 ,-1,0
       0      .1       0   552.3    .045       0   566.9      .1       0
Bank Sta=552.3,566.9
XS Rating Curve= 0 ,0
Exp/Cntr(USF)=0,0
Exp/Cntr=0.3,0.1

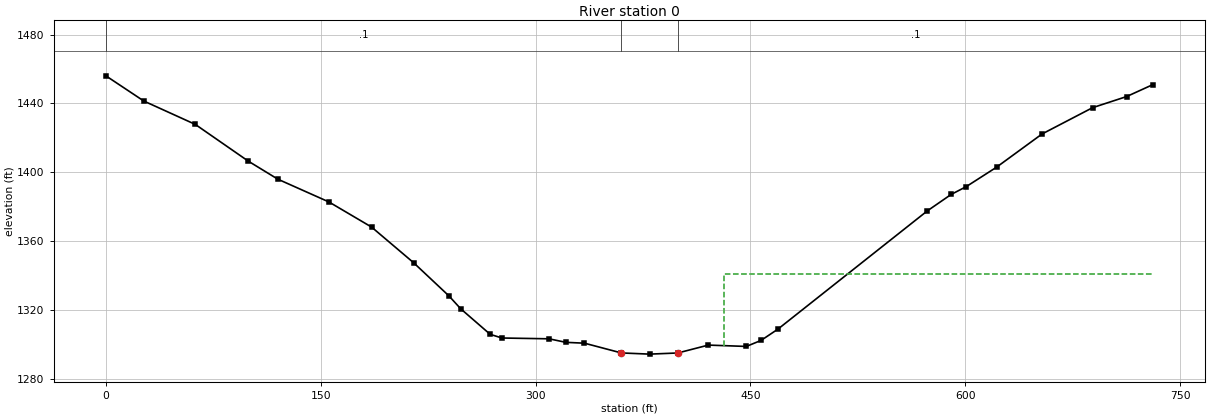
Type RM Length L Ch R = 1 ,0       ,844.8,844.8,844.8
XS GIS Cut Line= 4
2150675.49997512 675264.53581144 2150999.6589054675185.716345517
2151072.92770471675204.5886120052151283.85303606675447.707809714
#Sta/Elev= 30
       0 1456.02    26.5 1441.36    62.4  1427.8    99.4 1406.45   120.1 1395.94
   155.7 1382.74   185.5 1368.13   214.8 1347.45   239.5 1328.14   247.7 1320.67
   268.3 1305.81   276.5 1303.68   309.4 1303.21   321.2 1301.15   334.1 1300.67
   359.9    1295   379.6 1294.31   399.3 1294.98   420.6 1299.56   447.1 1298.78
   457.4 1302.27   469.2 1308.84   573.6 1377.61   590.1 1387.08   600.7 1391.65
   621.8 1402.91   653.6 1422.23   688.9 1437.52   712.6 1443.96   731.1 1450.97
#Mann= 3 ,-1,0
       0      .1       0   359.9    .045       0   399.3      .1       0
#XS Ineff= 2 , 0
                          431.34         1341.14
Permanent Ineff=
       F       F
Bank Sta=359.9,399.3
XS Rating Curve= 0 ,0
Exp/Cntr=0.3,0.1
LCMann Table=0

Chan Stop Cuts=-1
Use User Specified Reach Order=0
Composite Channel Slope=5