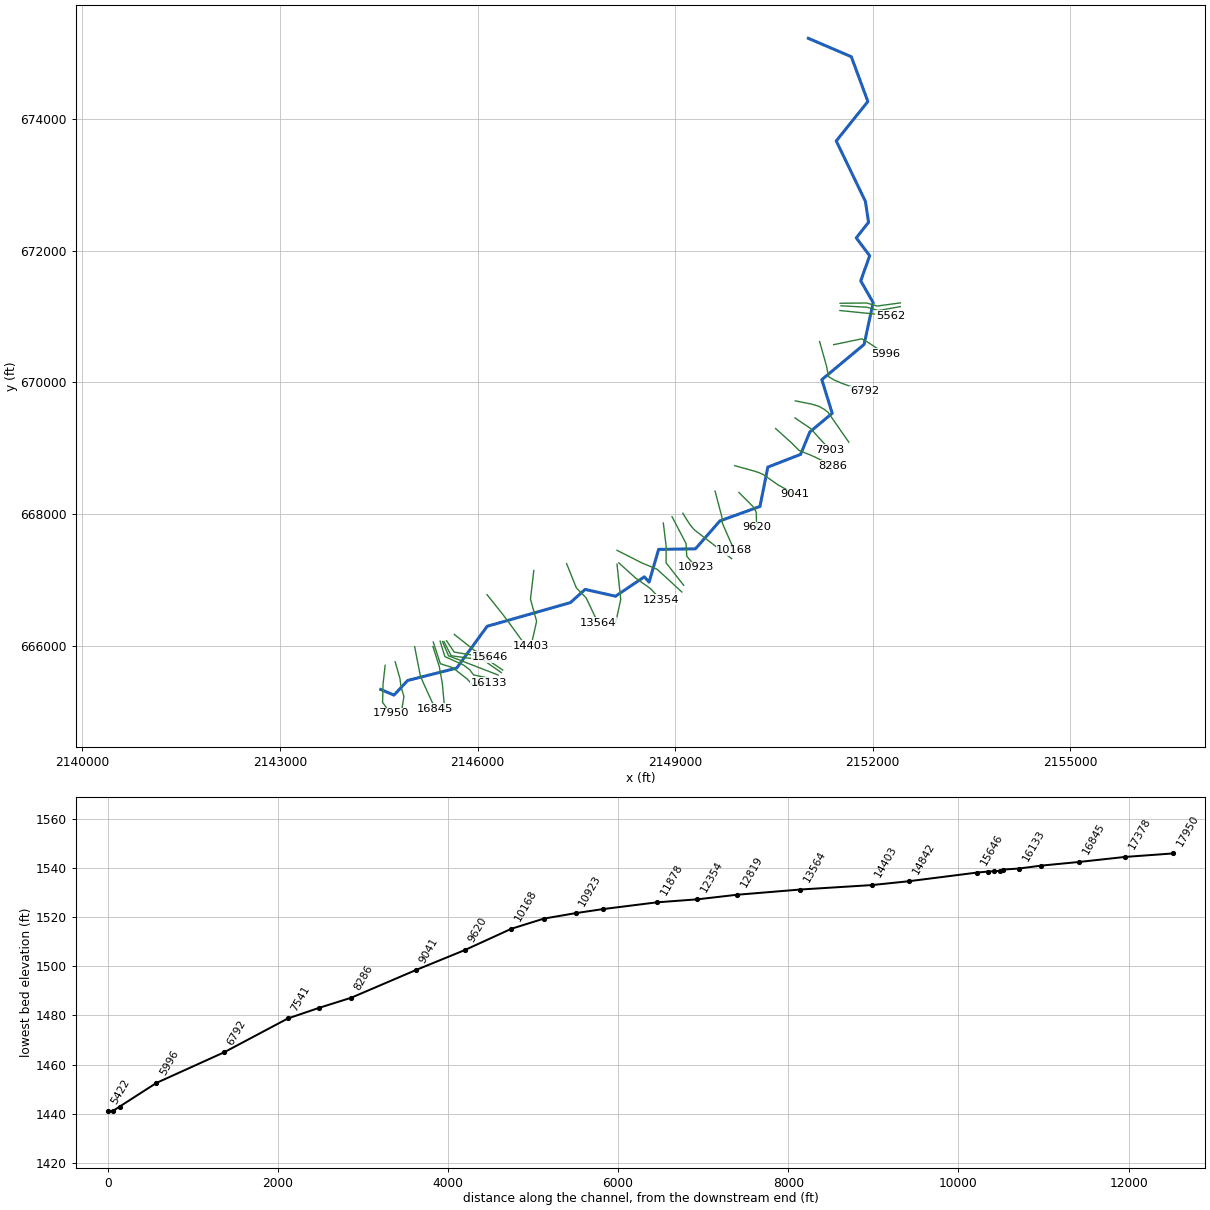
--- WHITECMPFK.prj (project) ---

Proj Title=WHITECMPFK
Current Plan=p01
Default Exp/Contr=0,0
English Units
Geom File=g01
Flow File=f01
Plan File=p01
BEGIN DESCRIPTION:
---------- MODELED AS PART OF WVEMD CTP PROGRAM, 2023----------
Stream Name: Whites Camp Fork
Flood Zone:  AFH
Upshur County, WV
HEC-RAS Version: RAS 6.3
Vertical Datum: NAVD88
Projection: NAD 1983 StatePlane West Virginia S FIPS 4702 (US Feet)
Terrain: 1-meter LIDAR (FEMA Region III 3DEP collected 2016-2018)
Land Use: 2019 NLCD
Hydrologic Method:
WV SIR2010-5033 regression equations
Additional Model Notes:
KWSE at DS boundark with WFORKRV due to name change and dominant flow path; leveraged DS XS
END DESCRIPTION:
DSS File=dss
DSS Export Rating Curves= 0
DSS Export Rating Curve Sorted= 0
DSS Export Volume Flow Curves= 0
DXF OffsetX= 0
DXF OffsetY= 0
DXF ScaleX= 0
DXF ScaleY= 0

--- WHITECMPFK.p01 (plan) ---

Plan Title=Floodplain
Program Version=6.31
Short Identifier=Floodplain
Geom File=g01
Flow File=f01
Subcritical Flow
K Sum by GR= 0
Std Step Tol= 0.01
Critical Tol= 0.01
Num of Std Step Trials= 20
Max Error Tol= 0.3
Flow Tol Ratio= 0.001
Split Flow NTrial= 30
Split Flow Tol= 0.02
Split Flow Ratio= 0.02
Log Output Level= 0
Friction Slope Method= 1
Unsteady Friction Slope Method= 2
Unsteady Bridges Friction Slope Method= 1
Parabolic Critical Depth
Global Vel Dist= 0 , 0 , 0
Global Log Level= 0
CheckData=True
Encroach Param=-1 ,0,0, 0
Computation Interval=0.1SEC
Output Interval=1SEC
Instantaneous Interval=Max Profile
Mapping Interval=1HOUR
Computation Time Step Use Courant=        0
Computation Time Step Use Time Series=    0
Computation Time Step Count To Double=0
Computation Time Step Max Doubling=0
Computation Time Step Max Halving=0
Computation Time Step Residence Courant=0
Run HTab= 0
Run UNet= 0
Run Sediment= 0
Run PostProcess= 0
Run WQNet= 0
Run RASMapper=-1
UNET Theta= 0
UNET Theta Warmup= 0
UNET ZTol= 0
UNET ZSATol= 0
UNET MxIter= 0
UNET Max Iter WO Improvement= 0
UNET MaxInSteps= 0
UNET DtIC= 0
UNET DtMin= 0
UNET MaxCRTS= 0
UNET WFStab= 0
UNET SFStab= 0
UNET WFX= 1
UNET SFX= 1
UNET Gravity=32.17405
UNET 1D Methodology=Finite Difference
UNET DSS MLevel= 1
UNET Pardiso=0
UNET DZMax Abort= 0
UNET Use Existing IB Tables= 0
UNET Froude Reduction=False
UNET Froude Limit= 0
UNET Froude Power= 0
UNET D1 Cores= 0
UNET WindReference=Eulerian
UNET WindDragFormulation=Hsu (1988)
UNET D2 Coriolis=0
UNET D2 Cores= 0
UNET D2 Theta= 1
UNET D2 Theta Warmup= 1
UNET D2 Z Tol= 0.01
UNET D2 Volume Tol= 0.01
UNET D2 Max Iterations= 20
UNET D2 Equation= 0
UNET D2 RampUpFraction=0.1
UNET D2 TimeSlices= 1
UNET D2 Turbulence Formulation=Non-Conservative (original)
UNET D2 Eddy Viscosity=0.3
UNET D2 Transverse Eddy Viscosity=0.1
UNET D2 Smagorinsky Mixing=0
UNET D2 BCVolumeCheck=0
UNET D2 Cores=0
UNET D2 SolverType=PARDISO (Direct)
UNET D2 Minimum Iterations= 3
UNET D2 Maximum Iterations= 30
UNET D2 Restart Number= 10
UNET D2 Relaxation Coeff=1.3
UNET D2 SOR Precondition Iterations= 10
UNET D2 ILUT Maximum Fill= 8
UNET D2 ILUT Tolerance=1E-08
UNET D2 Convergence Tolerance=0.00001
UNET D1D2 MaxIter= 0
UNET D1D2 ZTol=0.01
UNET D1D2 QTol=0.1
UNET D1D2 MinQTol=1
DSS File=dss
Write IC File= 0
Write IC File at Fixed DateTime=0
Write IC File at Sim End=0
Echo Input=False
Echo Parameters=False
Echo Output=False
Write Detailed= 0
HDF Write Warmup=0
HDF Write Time Slices=0
HDF Flush=0
HDF Compression= 1
HDF Chunk Size= 1
HDF Spatial Parts= 1
HDF Use Max Rows=0
HDF Fixed Rows= 1
Calibration Method= 0
Calibration Iterations= 20
Calibration Max Change=0.05
Calibration Tolerance=0.2
Calibration Maximum=1.5
Calibration Minimum=0.5
Calibration Optimization Method= 1
WQ AD Non Conservative
WQ ULTIMATE=-1
WQ Max Comp Step=1HOUR
WQ Output Interval=15MIN
WQ Output Selected Increments= 0
WQ Create Restart=0
WQ Fixed Restart=0
WQ System Summary=0
WQ Write To DSS=0
Sorting and Armoring Iterations= 10
XS Update Threshold= 0.02
Bed Roughness Predictor= 0
Hydraulics Update Threshold= 0.02
Energy Slope Method= 1
Volume Change Method= 1
Sediment Retention Method= 0
Sediment TS Multiplier= 1
Warm Up Method= 0
XS Weighting Method= 0
Number of US Weighted Cross Sections= 1
Number of DS Weighted Cross Sections= 1
Upstream XS Weight=0
Main XS Weight=1
Downstream XS Weight=0
Number of DS XS's Weighted with US Boundary= 1
Upstream Boundary Weight= 1
Weight of XSs Associated with US Boundary= 0
Number of US XS's Weighted with DS Boundary= 1
Downstream Boundary Weight= 0.5
Weight of XSs Associated with DS Boundary= 0.5
Percentile Method= 0
Sediment Output Level= 3
Mass or Volume Output= 0
Output Increment Type= 1
Profile and TS Output Increment= 1
Transport Output Increment 1
XS Output Flag= 0
XS Output Increment= 10
Read HDF5 Sediment Hotstart= 0
Sediment Hotstart Type= 0
Write Gradation File= 0
Read Gradation Hotstart= 0
Write HDF5 File= 1
Write Binary Output= 1
Write DSS Sediment File= 0
DSS Sediment Output Type= 1
SV Curve= 0
Specific Gage Flag= 0
Subcell Erosion Methods= 0
Subcell Deposition Methods= 0
Advection Scheme= 1
Matrix Solver= 0
Implicit Weighting Factor= 1
Maximum Outer Loop Convergence Iterations= 5
Convergence Maximum Absolute= 0.001
Convergence RMSE= 0.0001
Grain Fractions Max Abs Error= 0.001
Max Subgrid Regions= 1
Max Subgrid Length Scale= 3.402823E+38
Initial Layer Thickness= 3.402823E+38
Min Layer Thickness= 3.402823E+38
Max Layer Thickness= 3.402823E+38
Number of Layers= 5

--- WHITECMPFK.f01 (steady flow) ---

Flow Title=Flows
Program Version=6.31
Number of Profiles= 1
Profile Names=01pct
River Rch & RM=WHITECMPFK,Main            ,17950
     721
River Rch & RM=WHITECMPFK,Main            ,14403
     878
River Rch & RM=WHITECMPFK,Main            ,11249
     994
River Rch & RM=WHITECMPFK,Main            ,9620
    1110
River Rch & RM=WHITECMPFK,Main            ,7903
    1250
River Rch & RM=WHITECMPFK,Main            ,5422
    1390
River Rch & RM=WHITECMPFK,Main            ,0
    2060
Boundary for River Rch & Prof#=WHITECMPFK,Main            , 1
Up Type= 0
Dn Type= 1
Dn Known WS=1300.23
DSS Import GetInterval= 0
DSS Import GetPeak= 0
DSS Import FillOption= 0

--- WHITECMPFK.g01 (geometry) ---

Geom Title=Geometry
Program Version=6.31

River Reach=WHITECMPFK      ,Main
Reach XY= 30
2144530.28354859665334.9115945992144731.07400003665249.369000018
2144938.71400003665471.6330000012145682.82600003665659.757000014
2146146.35500005666295.2130000142147409.91100003      666654.978
2147633.00500001666855.5209999982148094.55800001666751.844000012
2148532.50399999667046.7929999982148605.07499999666966.725000009
2148749.21500002667463.5620000062149308.29400003667472.033000007
2149680.10700004667896.241999999     2150288.005668116.045000002
2150407.62100004668713.2399999952150905.48900001668907.431000009
2151044.96500003669246.850000009     2151385.214669531.754999995
2151227.30900002670042.0990000222151869.23200001670577.655000016
2152006.90499999671212.8820000142151817.92200002671543.601000011
2151953.87900002671924.7140000162151749.98700002672196.254999995
2151936.93800002 672433.142000022151888.74800001672751.499000013
     2151446.024673668.8830000012151926.52200001 674267.93900001
2151675.06900005674948.3789999932151022.55075881675228.016120592

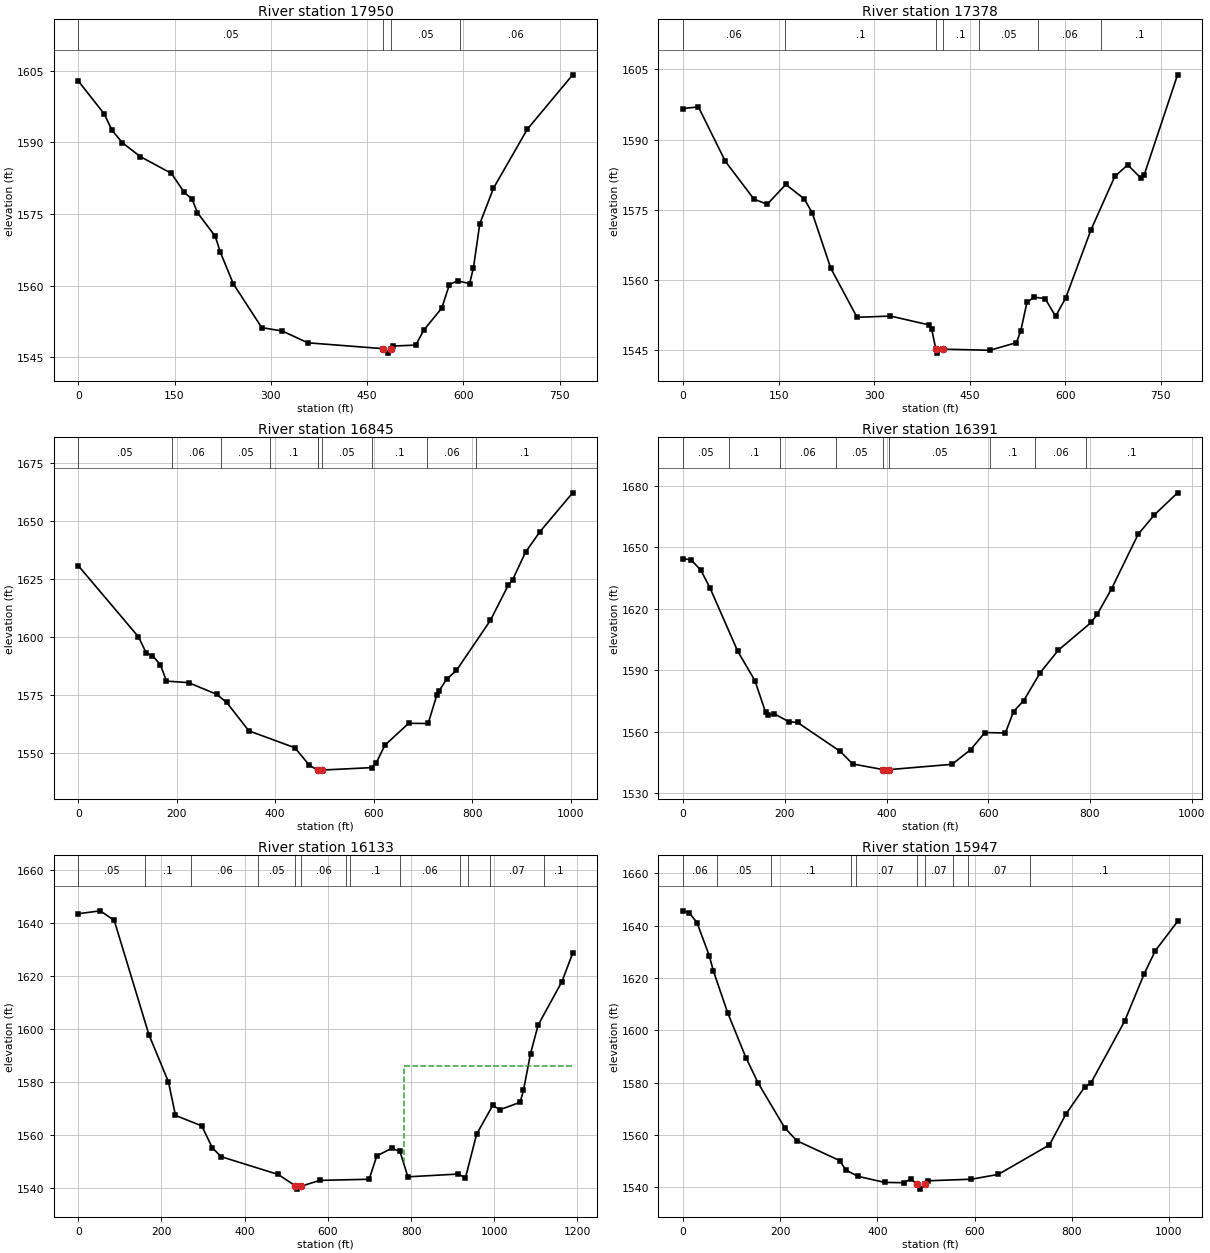
Type RM Length L Ch R = 1 ,17950   ,571.3,571.3,571.3
XS GIS Cut Line= 4
2144597.44788109665701.3598636082144565.62561895665420.745370245
2144558.32970191665138.9154234582144679.24608643664971.962455524
#Sta/Elev= 30
       0 1602.91    40.4 1595.99    52.5 1592.58    68.6 1589.96    96.8 1587.03
   145.1 1583.52   165.2 1579.52   177.3 1578.14   185.7 1575.28   213.5 1570.32
   221.6 1566.93   241.7 1560.34     286 1551.17     318 1550.47   357.5    1548
   474.5 1546.77     482 1545.83   487.4 1546.76     490 1547.31   526.1 1547.52
   538.1 1550.59   566.5 1555.27   578.4 1560.21   591.2 1560.98   609.9  1560.4
   615.9 1563.75   625.7 1572.92   647.1 1580.42   699.8 1592.77770.4783 1604.18
#Mann= 4 ,-1,0
       0     .05       0   474.5    .045       0   487.4     .05       0
  594.34     .06       0
Bank Sta=474.5,487.4
XS Rating Curve= 0 ,0
Exp/Cntr(USF)=0,0
Exp/Cntr=0.3,0.1

Type RM Length L Ch R = 1 ,17378   ,515.2,533.3,525.9
XS GIS Cut Line= 5
2144749.29236836665756.1836948482144822.00521451665501.085069761
2144837.37638532665382.6402670932144882.12536493665226.548781067
2144845.40631172664999.864664928
#Sta/Elev= 30
       0 1596.65    23.9    1597    66.3 1585.36   111.3 1577.28   132.1  1576.2
   161.2 1580.42   190.3 1577.35   202.8 1574.34   231.9 1562.53   273.2 1552.04
   325.7 1552.31   386.2 1550.42   390.4 1549.48     3971545.265   398.7 1544.39
   407.5 1545.24   481.9    1545   523.5 1546.63   530.4 1549.16   540.1 1555.24
   551.2 1556.36   568.7 1556.04   585.1 1552.25   601.1 1556.22   640.6 1570.71
   678.1 1582.14   698.4 1584.61   718.7 1581.85   724.3 1582.48   776.7 1603.85
#Mann= 7 ,-1,0
       0     .06       0     160      .1       0     397    .045       0
   407.5      .1       0   464.7     .05       0  557.08     .06       0
  657.08      .1       0
Bank Sta=397,407.5
XS Rating Curve= 0 ,0
Exp/Cntr(USF)=0,0
Exp/Cntr=0.3,0.1

Type RM Length L Ch R = 1 ,16845   ,448.7,454.3,444.3
XS GIS Cut Line= 4
2145045.00063989665985.065201958 2145132.7529385665537.624910134
2145198.32608471665389.1210201742145358.40170636665038.111825726
#Sta/Elev= 30
       0 1630.92   122.2 1600.26   138.5 1593.12   150.7 1592.19     167 1588.12
   179.2 1581.17   224.1  1580.5   281.1 1575.47   301.5 1571.96   346.4 1559.74
   440.1 1552.43   469.6 1544.83   486.41542.818   491.4 1542.37   495.3 1542.83
   596.4 1543.89   605.1 1545.85   622.6 1553.52     671 1562.97   710.6 1562.91
   728.1 1575.06   732.5 1576.89   748.1 1581.98     768 1585.74     837 1607.34
   873.2 1622.44     882 1624.77   908.4 1636.73   937.7 1645.58  1004.1 1662.31
#Mann= 10 ,-1,0
       0     .05       0     190     .06       0     290     .05       0
     390      .1       0  485.96     .05       0   486.4    .045       0
   495.3     .05       0  595.96      .1       0   708.3     .06       0
   808.3      .1       0
Bank Sta=486.4,495.3
XS Rating Curve= 0 ,0
Exp/Cntr(USF)=0,0
Exp/Cntr=0.3,0.1

Type RM Length L Ch R = 1 ,16391   ,257.8,257.8,257.8
XS GIS Cut Line= 4
2145323.01823248665987.6830951222145418.81952483665684.500902495
2145464.47946078665433.7436188352145501.70004934665035.985278174
#Sta/Elev= 30
       0 1644.36    15.2 1644.01    34.8 1638.86      53 1630.09   107.5 1599.22
   141.1 1585.03     162 1569.59   166.2 1568.11   178.8 1568.84   208.2 1564.93
     225 1564.59   308.9 1550.48   333.5 1544.33  393.44 1541.59   398.6 1540.85
   404.9 1541.58   528.7 1544.17   565.3 1551.31   593.5 1559.67   633.7 1559.45
   649.7 1569.89   669.8 1575.26   702.3 1588.92   738.1 1599.91   802.4 1613.37
   814.5 1617.42   842.6 1629.83   894.8  1656.4   926.9 1665.89   972.3  1676.6
#Mann= 9 ,-1,0
       0     .05       0      90      .1       0     190     .06       0
     300     .05       0  393.44    .045       0   404.9     .05       0
  602.84      .1       0  692.84     .06       0  792.84      .1       0
Bank Sta=393.44,404.9
XS Rating Curve= 0 ,0
Exp/Cntr(USF)=0,0
Exp/Cntr=0.3,0.1

Type RM Length L Ch R = 1 ,16133   ,186,186,186
XS GIS Cut Line= 6
  2145327.798029 666055.245539552145435.65134947665726.519775501
2145623.50508861665665.958296558 2145839.0870804665497.362123485
 2145922.0032311665408.9182294142146169.83039261665434.714365184
#Sta/Elev= 30
       0 1643.56    52.7 1644.66    86.4 1641.07   169.9 1597.92   216.9 1580.08
   233.7 1567.49   296.9 1563.53   322.1 1555.31   343.2 1551.93   480.6 1545.21
     5211541.008   526.9 1539.68   536.21540.816   580.7 1542.97   699.2 1543.41
   717.7 1552.23   753.4 1555.07   773.3 1553.89   792.3 1544.32   913.2 1545.37
   930.7 1543.96   957.5 1560.38   996.1 1571.23  1013.8 1569.66  1062.1 1572.43
  1070.1 1576.91  1087.1 1590.79  1105.4 1601.58  1162.6 1617.95  1188.4 1628.66
#Mann= 13 ,-1,0
       0     .05       0     160      .1       0     270     .06       0
  433.21     .05       0     521    .045       0   536.2     .06       0
  644.25     .05       0  654.25      .1       0  774.25     .06       0
  917.99     .07       0  937.99      .1       0  989.23     .07       0
 1119.23      .1       0
#XS Ineff= 2 , 0
                          782.03         1586.14
Permanent Ineff=
       F       F
Bank Sta=521,536.2
XS Rating Curve= 0 ,0
Exp/Cntr(USF)=0,0
Exp/Cntr=0.3,0.1

Type RM Length L Ch R = 1 ,15947   ,33.2,35.6,38.6
XS GIS Cut Line= 6
2145431.87665145666068.5622726952145504.65860595665834.554469632
 2145786.5735183665706.4950813412145880.54515575665635.555707971
 2145939.5077518665556.3247195332146179.04329824665505.653738554
#Sta/Elev= 30
       0  1645.7    12.5 1644.97    28.5 1641.17    53.8 1628.52    62.2 1622.73
    91.5  1606.8   129.2 1589.56   154.3 1579.85   208.8 1562.81   233.9 1557.78
   322.3 1550.18     335 1546.54   360.4 1544.14   414.5 1541.85   454.4 1541.72
   468.9 1543.18  481.26 1541.08   487.4 1539.27   497.7 1541.15   503.5 1542.46
   593.5 1543.06   648.7  1544.9     754 1556.17   788.1 1567.98   826.8 1578.38
     839 1579.73   908.6 1603.41   949.4 1621.72   971.9  1630.4  1017.8 1641.65
#Mann= 10 ,-1,0
       0     .06       0      70     .05       0     180      .1       0
  345.07     .06       0  355.07     .07       0  481.26    .045       0
   497.7     .07       0  556.25     .06       0  586.44     .07       0
  714.18      .1       0
Bank Sta=481.26,497.7
XS Rating Curve= 0 ,0
Exp/Cntr(USF)=0,0
Exp/Cntr=0.3,0.1

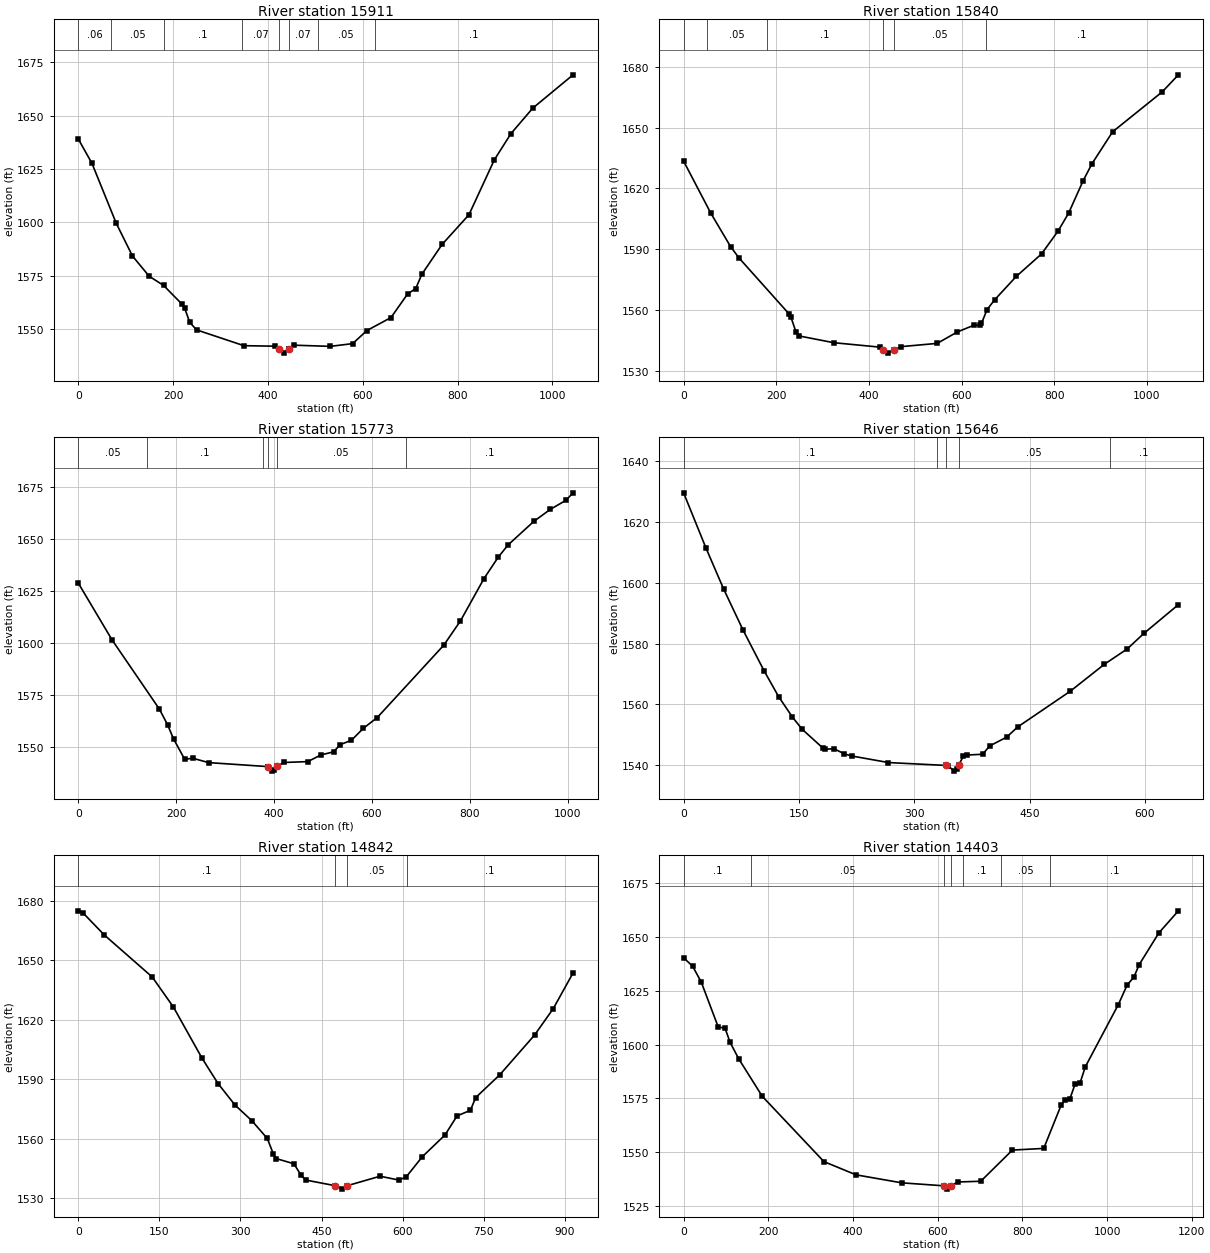
Type RM Length L Ch R = 1 ,15911   ,64.2,71.3,76.7
XS GIS Cut Line= 3
2145467.87043615666062.7950329912145559.90736342665846.383879685
 2146313.6151732 665554.51902925
#Sta/Elev= 30
       0  1639.1    28.9 1627.67      80 1599.61   114.3 1584.24   149.5 1574.77
     180 1570.43   219.1  1561.6   224.1 1559.93   235.2 1553.08   249.6 1549.61
   349.3 1542.21   415.6 1541.97   424.31540.651   432.8 1538.72   443.5 1540.62
   443.5 1540.64   454.2 1542.45   531.4 1541.89   578.6 1543.18   608.6 1549.31
   659.4 1555.39   694.4 1566.44   711.6    1569   724.5 1575.69   767.3 1589.71
   823.8 1603.59   877.5  1629.4   912.5 1641.66   958.5 1653.59  1043.4 1669.19
#Mann= 8 ,-1,0
       0     .06       0      70     .05       0     180      .1       0
  345.17     .07       0   424.3    .045       0   443.5     .07       0
  505.17     .05       0  625.17      .1       0
Bank Sta=424.3,443.5
XS Rating Curve= 0 ,0
Exp/Cntr(USF)=0,0
Exp/Cntr=0.3,0.1

Type RM Length L Ch R = 1 ,15840   ,71,67.2,60.3
XS GIS Cut Line= 4
2145489.42863533666063.6241944982145599.70711575665847.213041192
2146090.57072784665780.880120639 2146360.8773791665591.831297061
#Sta/Elev= 30
       0  1633.4    58.9 1607.62   101.5 1591.16   119.5 1585.61   227.2 1558.06
   231.7 1556.33   242.9 1548.85   248.7 1547.11   324.1 1543.75     425 1541.53
  431.34 1540.16   440.7  1538.6   453.3 1540.18   469.4  1541.8   547.4 1543.41
   591.1 1549.08   626.8 1552.39   638.9 1552.36     643 1553.29   655.1 1560.11
   671.2 1564.87     718 1576.45   772.6 1587.58   808.5 1598.93   831.1 1607.73
   862.2 1623.62   881.7 1632.19   926.1 1647.89    1033 1667.57  1068.1 1676.02
#Mann= 6 ,-1,0
       0     .06       0      50     .05       0     180      .1       0
  431.34    .045       0   453.3     .05       0  652.89      .1       0
Bank Sta=431.34,453.3
XS Rating Curve= 0 ,0
Exp/Cntr(USF)=0,0
Exp/Cntr=0.3,0.1

Type RM Length L Ch R = 1 ,15773   ,131.9,126.3,118.4
XS GIS Cut Line= 4
2145530.05754917666074.4032940882145646.14016014665902.766862156
2146091.39988935 665828.971488042146382.43557828665630.801887886
#Sta/Elev= 30
       0 1628.91    69.1 1601.54   165.7 1568.27   182.3  1560.8   194.6 1553.95
   217.4 1544.13   233.6 1544.68     266 1542.56   387.7 1540.63   387.7 1540.61
   395.8 1538.46   399.8 1538.84   405.1 1540.72   420.1 1542.62   468.8 1543.04
   495.6 1546.25   521.5 1547.73   534.9 1551.19     558 1553.33   582.3 1559.05
   610.7 1564.25   746.6 1599.06   780.5 1610.69   828.7  1631.1   857.6 1641.32
   877.7 1647.23   930.5  1658.6   964.3 1664.39   995.8 1668.69  1010.6 1672.32
#Mann= 6 ,-1,0
       0     .05       0     140      .1       0  377.21     .05       0
   387.7    .045       0   405.1     .05       0  668.54      .1       0
Bank Sta=387.7,405.1
XS Rating Curve= 0 ,0
Exp/Cntr(USF)=0,0
Exp/Cntr=0.3,0.1

Type RM Length L Ch R = 1 ,15646   ,801,803.9,797
XS GIS Cut Line= 3
2145647.36669499666171.2906856122145956.32624664665926.168670344
2146185.40229817665827.773587809
#Sta/Elev= 30
       0 1629.63    29.1 1611.46    52.1 1597.97    77.6 1584.34   104.6 1571.12
   123.6 1562.58   141.6 1555.83   154.2 1551.85   181.4 1545.61   184.3 1545.27
   195.7 1545.44   209.3 1543.72   218.5 1543.06   266.5 1540.89   340.9 1539.95
   344.5 1539.67   352.3 1538.07   355.1 1538.68   357.7 1539.95   363.7  1542.9
   368.7 1543.37   389.1 1543.62   398.1 1546.35   420.3 1549.26   434.6  1552.6
   503.1 1564.37   547.3 1573.21   577.1 1578.27   598.8 1583.38   643.7 1592.85
#Mann= 5 ,-1,0
       0      .1       0     330     .05       0   340.9    .045       0
   357.7     .05       0  554.39      .1       0
Bank Sta=340.9,357.7
XS Rating Curve= 0 ,0
Exp/Cntr(USF)=0,0
Exp/Cntr=0.3,0.1

Type RM Length L Ch R = 1 ,14842   ,442.4,439.5,431.4
XS GIS Cut Line= 4
2146143.65286374666776.1201692242146387.42686964666470.458366605
2146487.61693305666336.3597007332146697.40311101666047.457957557
#Sta/Elev= 30
       0 1675.08     8.9 1673.99      48 1662.92   136.8 1641.67   176.1 1626.45
   228.9 1600.67   258.6 1587.84   289.9 1577.01     321 1569.13   349.7 1560.12
   361.1 1552.17   366.5 1549.94   398.9 1547.35   412.5 1541.43     421 1539.12
   475.3 1536.27   487.4 1534.54   497.4 1536.26   558.4 1541.06   593.3  1539.1
   606.9 1540.79   636.4 1550.87   678.5  1561.9   700.7  1571.5   725.4 1574.34
   735.3 1580.79   779.8 1592.27   844.1 1612.32   878.7 1625.68   915.4 1643.72
#Mann= 4 ,-1,0
       0      .1       0   475.3    .045       0   497.4     .05       0
  608.36      .1       0
Bank Sta=475.3,497.4
XS Rating Curve= 0 ,0
Exp/Cntr(USF)=0,0
Exp/Cntr=0.3,0.1

Type RM Length L Ch R = 1 ,14403   ,825.3,838.6,844.3
XS GIS Cut Line= 4
2146854.07850053667142.3640695972146803.79228902666705.311055517
2146897.07176532666372.0013969422146812.57564599665998.913450442
#Sta/Elev= 30
       0 1640.26    21.3 1636.33    41.5 1629.06    81.7 1608.18    97.8  1607.6
   109.9 1600.98     130 1593.44   185.7 1576.02   331.4 1545.72   407.2 1539.59
     515 1535.88   614.5  1534.5   622.8 1532.96   631.31534.557   647.8 1536.28
   701.8 1536.61   776.5 1551.07   850.5 1551.84   891.5 1571.85   899.9 1574.08
     912 1574.68   924.3 1581.49   936.6 1582.39   948.9 1589.76  1026.8 1618.58
  1047.3 1627.54  1063.7 1631.38    1076  1637.1  1122.6 1651.84  1168.6 1662.03
#Mann= 7 ,-1,0
       0      .1       0     160     .05       0   614.5    .045       0
   631.3     .05       0  659.94      .1       0  749.94     .05       0
  866.05      .1       0
Bank Sta=614.5,631.3
XS Rating Curve= 0 ,0
Exp/Cntr(USF)=0,0
Exp/Cntr=0.3,0.1

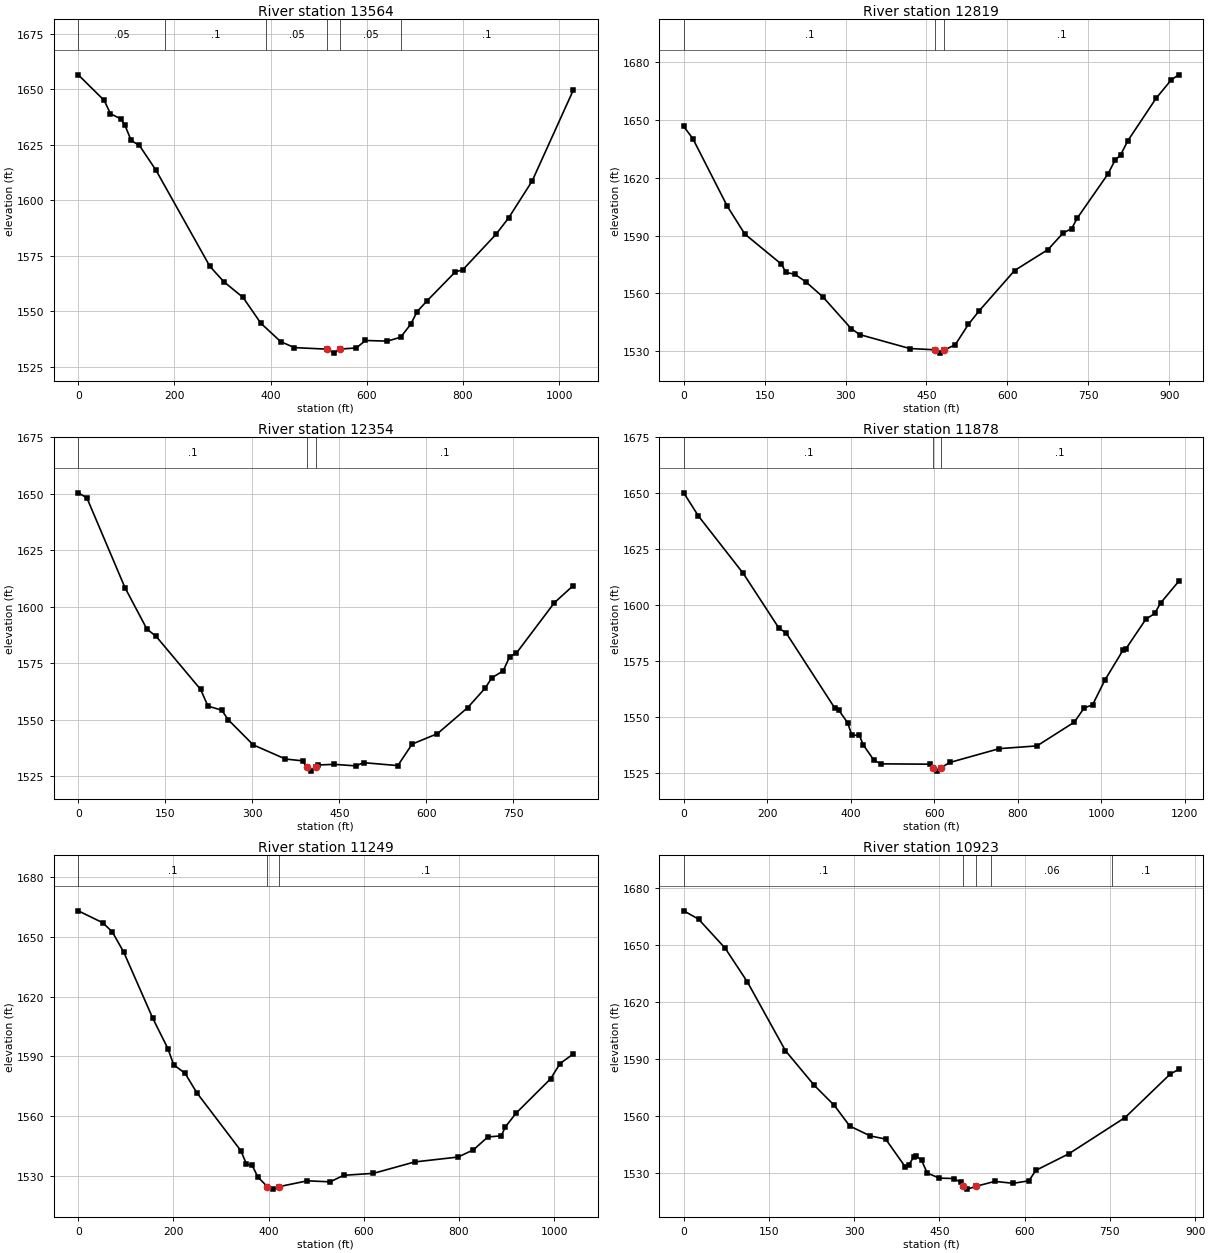
Type RM Length L Ch R = 1 ,13564   ,745.1,745.4,719.8
XS GIS Cut Line= 4
2147352.32266536667247.2435131432147500.67636634666877.268341005
2147649.33933822666726.5448161092147828.74322033666347.690662483
#Sta/Elev= 30
       0 1656.58    53.9 1645.05    66.9 1639.06    88.4 1636.73      97 1633.88
     110    1627   127.2 1624.74   161.7 1613.57   273.7 1570.27   302.9  1563.3
   342.7 1556.27   379.8 1544.62   420.9 1536.36   449.3 1533.65   517.5 1532.95
   531.3 1531.16   544.8 1532.98   578.5 1533.51   597.3 1536.86   642.8 1536.57
   670.5 1538.33   691.6 1544.19   704.8 1549.87   724.9 1554.59   784.4  1567.8
   799.7 1568.68   868.8 1584.68   895.1 1592.07   944.1 1608.73  1029.5 1649.59
#Mann= 6 ,-1,0
       0     .05       0     180      .1       0     390     .05       0
   517.5    .045       0   544.8     .05       0  670.31      .1       0
Bank Sta=517.5,544.8
XS Rating Curve= 0 ,0
Exp/Cntr(USF)=0,0
Exp/Cntr=0.3,0.1

Type RM Length L Ch R = 1 ,12819   ,446.6,464.6,465.7
XS GIS Cut Line= 3
2148117.38713019667237.7502537542148174.54708319666703.463783753
2148092.84662236666332.114272618
#Sta/Elev= 30
       0 1646.64    16.7  1640.4      81 1605.12   113.2 1590.82   181.1 1575.18
   189.6 1570.88   205.7    1570   225.9 1566.12     258 1558.21   310.3 1541.77
   326.4 1538.63   418.9 1531.43     466 1530.75   475.3 1529.03   483.3 1530.71
   503.4 1533.38   527.6 1543.92   547.7 1550.97   613.4  1571.9   675.5  1582.8
   703.5 1591.42   719.2 1593.64   729.2 1598.94   786.3 1621.92   799.7 1629.15
     810 1631.88   823.2 1639.17   875.5 1661.18   903.8 1670.82   917.6 1673.44
#Mann= 3 ,-1,0
       0      .1       0     466    .045       0   483.3      .1       0
Bank Sta=466,483.3
XS Rating Curve= 0 ,0
Exp/Cntr(USF)=0,0
Exp/Cntr=0.3,0.1

Type RM Length L Ch R = 1 ,12354   ,468.8,476.6,474.5
XS GIS Cut Line= 4
2148144.51060771667259.0722432072148396.65154965667031.234193981
2148630.41362527666863.8952868442148782.79856927666697.224254345
#Sta/Elev= 30
       0 1650.42    14.8  1648.2    80.4 1608.47   118.2 1590.12   134.1 1586.88
   210.7 1563.41   223.6 1555.98   247.4 1554.17   258.3 1549.96   301.5 1538.81
   357.1 1532.54   386.8 1531.73  393.64 1528.88   401.2 1527.18   409.8 1528.92
     413  1529.9   441.3 1530.18   478.6  1529.5   491.7 1530.93   550.8 1529.63
   575.4 1539.15   619.1 1543.77   671.4 1555.34   701.3 1563.93   712.9 1568.52
   732.4 1571.58   743.7 1577.94   755.1 1579.41   820.7 1601.77   853.1 1609.32
#Mann= 3 ,-1,0
       0      .1       0  393.64    .045       0   409.8      .1       0
Bank Sta=393.64,409.8
XS Rating Curve= 0 ,0
Exp/Cntr(USF)=0,0
Exp/Cntr=0.3,0.1

Type RM Length L Ch R = 1 ,11878   ,636.9,628.8,586.3
XS GIS Cut Line= 4
 2148116.9848911667449.7636396482148504.68381547667253.313920338
2148726.57989266 667162.009787522149102.29947542666815.775681838
#Sta/Elev= 30
       0 1650.25      35 1639.92   142.6 1614.25   227.8 1589.86   245.7 1587.55
   362.3 1553.94   371.9 1553.04   392.7 1547.48   402.7 1541.97   420.6 1541.97
   429.6 1537.82   455.8 1530.71     473  1529.2   589.8 1529.05   596.8 1527.32
   607.1 1525.95   615.1 1527.34   637.4 1529.82   755.6 1535.99   846.1 1537.22
   935.5 1547.82   959.1 1554.18   979.2 1555.53  1008.5 1566.51  1052.1 1579.95
  1059.5 1580.69  1106.7 1593.75  1128.2  1596.4  1142.1 1601.02  1185.5  1610.7
#Mann= 3 ,-1,0
       0      .1       0   596.8    .045       0   615.1      .1       0
Bank Sta=596.8,615.1
XS Rating Curve= 0 ,0
Exp/Cntr(USF)=0,0
Exp/Cntr=0.3,0.1

Type RM Length L Ch R = 1 ,11249   ,324.8,326.4,326.8
XS GIS Cut Line= 4
2148820.56978862667864.1081933092148862.88372663667518.129523733
2148862.88372663667259.2677853452149129.21263054666918.267226122
#Sta/Elev= 30
       0 1663.16    51.3 1657.17    71.5 1652.57    95.6 1642.34   156.7 1609.06
   188.3  1593.9   200.4 1585.79   224.6 1581.41   248.8 1571.78   341.5  1542.6
   353.5 1535.79   365.5 1535.15   377.5 1529.26   397.5 1524.46   409.5 1523.23
   421.5 1524.46   481.5 1527.41   529.5 1526.89   557.5 1530.18   620.2 1531.16
     707  1536.9     798 1539.36   830.5    1543   860.6 1549.46   888.9 1550.02
   897.6 1554.54   920.4 1561.52   992.9 1578.78  1012.4 1586.38  1040.1 1591.15
#Mann= 3 ,-1,0
       0      .1       0   397.5    .045       0   421.5      .1       0
Bank Sta=397.5,421.5
XS Rating Curve= 0 ,0
Exp/Cntr(USF)=0,0
Exp/Cntr=0.3,0.1

Type RM Length L Ch R = 1 ,10923   ,358.1,372.4,383.3
XS GIS Cut Line= 4
2148953.07598742667960.2384260042149166.07778687 667551.64398431
2149176.49137612667359.308260032 2149317.7121431 667193.74273137
#Sta/Elev= 30
       0  1668.1      26 1663.73    72.8 1648.45   111.7 1630.81   178.9 1594.48
   229.9 1576.14   265.1 1565.61   292.1 1554.78   328.2 1549.58   355.3 1547.91
     390 1533.21     396 1534.36   404.9 1538.52   409.4 1538.87   418.5 1536.71
   428.6 1529.99     450 1527.35   475.3 1527.14   487.3 1525.19   491.3  1523.1
   499.3 1521.56   514.5 1523.05   547.4 1525.64   579.8 1524.63   607.5 1525.95
   619.5 1531.42   677.6 1540.15   776.7 1559.26   856.1 1582.14     871 1584.62
#Mann= 5 ,-1,0
       0      .1       0   491.3    .045       0   514.5      .1       0
  540.78     .06       0   753.4      .1       0
Bank Sta=491.3,514.5
XS Rating Curve= 0 ,0
Exp/Cntr(USF)=0,0
Exp/Cntr=0.3,0.1

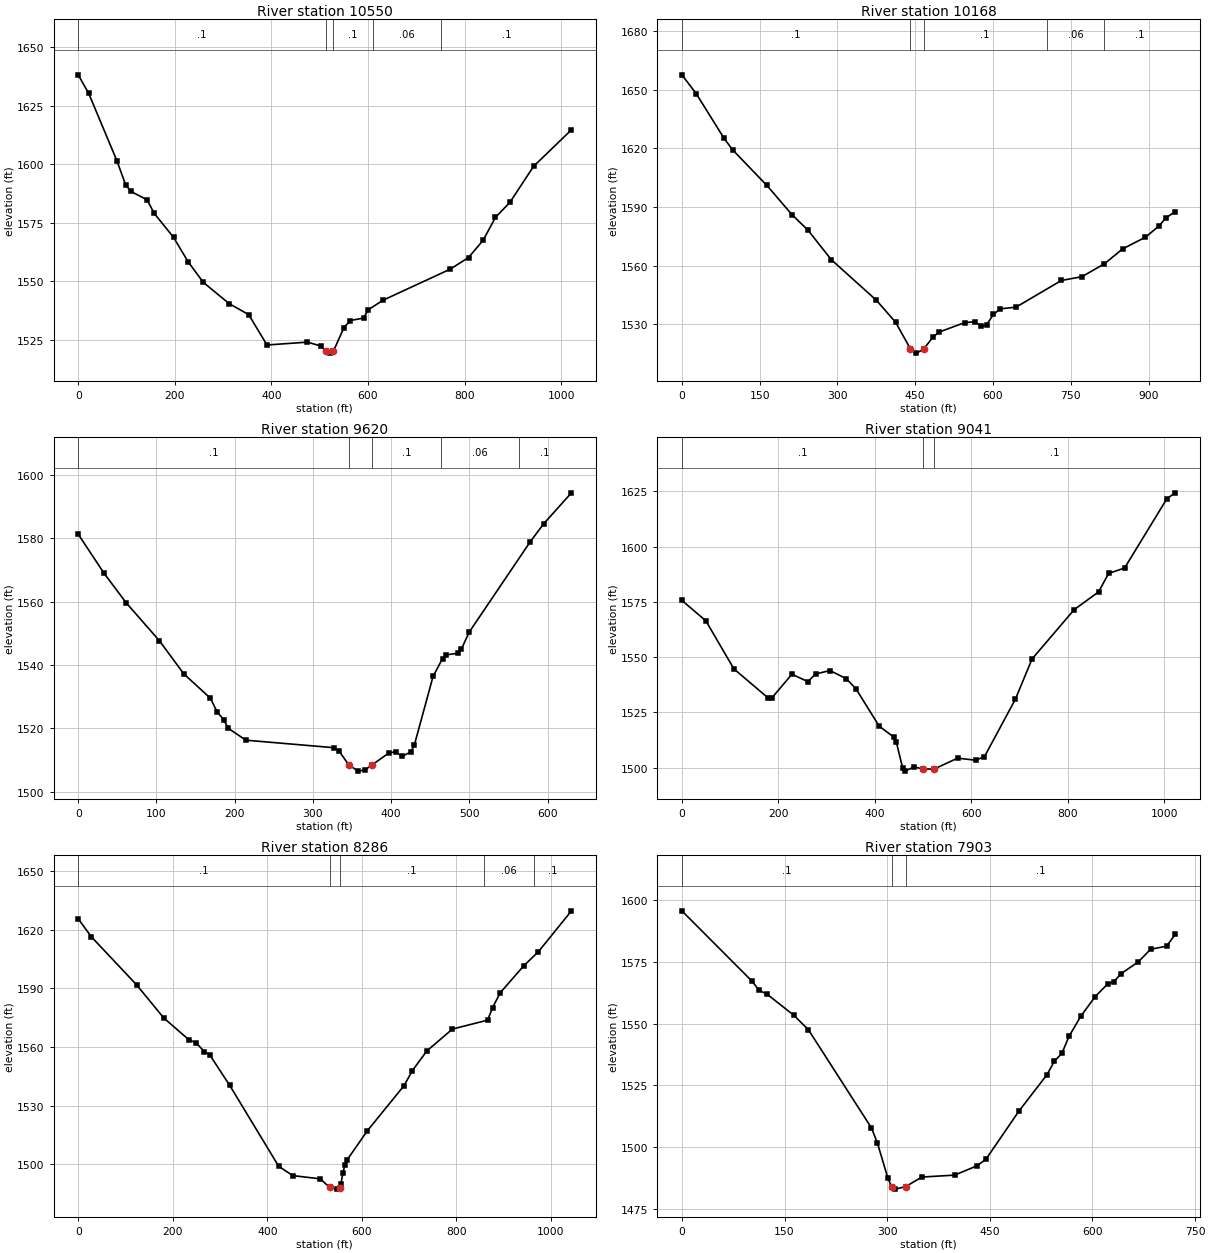
Type RM Length L Ch R = 1 ,10550   ,397,382.6,368.4
XS GIS Cut Line= 6
2149117.81552051668012.5350993422149172.92499034667920.247226179
2149229.81792118667833.5213497582149291.81910951667760.446036592
2149778.80599642667383.8326165832149856.67460708667323.612920761
#Sta/Elev= 30
       0  1638.1    21.7 1630.19      80 1601.49    98.2 1591.16   109.2 1588.33
   142.6 1584.77   157.2 1579.03   197.3 1568.77   227.2 1558.44   258.9 1549.56
   312.4 1540.48     353 1535.77   390.8 1522.82   474.4 1524.04     502 1522.41
   512.21520.192   520.6 1519.35   528.2 1520.14   550.2 1530.27   563.4 1533.25
   590.7 1534.33   600.8 1537.92   631.1 1541.93   770.1 1555.18   808.1 1560.15
   838.4 1567.57   863.7 1577.26   894.1 1583.79   942.6 1599.04  1021.1 1614.65
#Mann= 5 ,-1,0
       0      .1       0   512.2    .045       0   528.2      .1       0
  609.55     .06       0  752.05      .1       0
Bank Sta=512.2,528.2
XS Rating Curve= 0 ,0
Exp/Cntr(USF)=0,0
Exp/Cntr=0.3,0.1

Type RM Length L Ch R = 1 ,10168   ,534.2,547.3,548.5
XS GIS Cut Line= 4
2149606.43639179668347.866800381 2149709.3216281667959.049872338
2149718.40248789667857.7548537962149898.98534521667448.548256859
#Sta/Elev= 30
       0 1657.64    27.6 1648.06    81.4 1625.14    97.9 1619.25   164.1    1601
     213 1585.88   242.8 1578.29   288.3    1563   375.2 1542.26   412.1 1531.04
   440.8 1517.38   452.3 1515.21   466.21517.228   484.4 1523.47   496.4 1526.02
   545.1 1530.79   565.7 1531.28   577.6 1528.91   587.6 1529.62   600.7 1535.01
   613.8 1537.86   644.4 1538.74   731.9  1552.4   771.2 1554.31     815 1560.95
   849.9 1568.54   893.7  1574.5   919.9 1580.21     933  1584.3   951.2 1587.65
#Mann= 5 ,-1,0
       0      .1       0   440.8    .045       0   466.2      .1       0
   703.9     .06       0   813.9      .1       0
Bank Sta=440.8,466.2
XS Rating Curve= 0 ,0
Exp/Cntr(USF)=0,0
Exp/Cntr=0.3,0.1

Type RM Length L Ch R = 1 ,9620    ,563.3,579.1,587
XS GIS Cut Line= 4
  2149968.654131668328.6046776352150196.87439479668100.384413848
2150231.16100719668027.5253624992150238.66120365 667800.37655535
#Sta/Elev= 30
       0 1581.23    33.2 1568.85    61.5 1559.55   103.9 1547.62     135  1537.2
     169 1529.53   177.4  1525.3   185.9 1522.77   191.7 1520.08   214.3 1516.31
   327.6 1513.93   333.7  1512.8   345.7 1508.57   357.7 1506.56   366.1 1506.87
   375.7 1508.52   396.8 1512.24   405.6 1512.68   413.6 1511.21   425.6 1512.65
   429.8 1514.91   453.6 1536.41   465.7 1542.04   469.7 1543.19   485.7  1543.7
   489.7 1544.96   499.8 1550.37   577.7 1578.81     595 1584.51   630.5 1594.26
#Mann= 5 ,-1,0
       0      .1       0   345.7    .045       0   375.7      .1       0
  463.28     .06       0  563.28      .1       0
Bank Sta=345.7,375.7
XS Rating Curve= 0 ,0
Exp/Cntr(USF)=0,0
Exp/Cntr=0.3,0.1

Type RM Length L Ch R = 1 ,9041    ,750.2,755.1,755.1
XS GIS Cut Line= 6
2149904.43172942 668735.31482175 2150190.9200016668655.937027752
2150276.77153592668628.3104425822150345.20282951668595.448303595
  2150560.452399668445.2031972562150818.87642284 668299.92920959
#Sta/Elev= 30
       0 1575.67    49.7 1566.46   107.9 1544.67   178.4 1531.59   186.7 1531.55
   228.1 1542.25   261.3  1538.9   277.3 1542.37     307 1543.92   340.6 1540.28
   360.9 1535.65     409 1518.75   440.1 1513.68   444.5 1511.63   457.8 1499.65
   462.2 1498.38   481.7 1500.31   499.4 1499.31   522.9 1499.32   571.6 1504.25
   608.9 1503.33   627.3 1504.93   691.2 1530.86   725.9 1549.15   813.2 1571.49
   863.8 1579.53   884.6 1587.87   917.8 1590.36  1005.4  1621.7  1022.5 1624.39
#Mann= 3 ,-1,0
       0      .1       0   499.4    .045       0   522.9      .1       0
Bank Sta=499.4,522.9
XS Rating Curve= 0 ,0
Exp/Cntr(USF)=0,0
Exp/Cntr=0.3,0.1

Type RM Length L Ch R = 1 ,8286    ,386.4,383.3,372.5
XS GIS Cut Line= 6
2150525.48527734669299.7172362512150758.23842075 669090.45617184
2150884.18567543668965.3333905942151046.83069134668900.107143089
2151126.99391684668864.6449436692151386.13939592668734.742316335
#Sta/Elev= 30
       0 1625.69    27.8 1616.46   123.6 1591.82   181.1 1574.84   234.9 1563.55
   249.1 1562.22   267.1 1557.59   277.9 1556.11   320.6  1540.3   424.1  1498.9
   453.9 1494.14     512 1492.48   532.2 1488.07     547 1487.21   552.8    1488
   555.7 1489.81     560 1495.68   564.3 1499.76   568.7 1502.15   611.7 1517.12
   689.2  1540.2   706.7 1547.84   737.3 1557.95   791.6 1569.19     866 1573.76
   876.6 1580.23   892.8 1587.82     942 1601.46   973.5 1608.83  1043.4 1629.75
#Mann= 5 ,-1,0
       0      .1       0   532.2    .045       0   552.8      .1       0
  857.51     .06       0   964.7      .1       0
Bank Sta=532.2,552.8
XS Rating Curve= 0 ,0
Exp/Cntr(USF)=0,0
Exp/Cntr=0.3,0.1

Type RM Length L Ch R = 1 ,7903    ,363.2,362,359.2
XS GIS Cut Line= 3
2150819.18338726669460.9623689062151054.90384751 669301.31532992
2151348.48296618668978.806882036
#Sta/Elev= 30
       0 1595.61   102.6 1567.13   112.9 1563.41   124.3 1561.94   163.7 1553.34
   184.9 1547.52   277.1 1507.77   285.7 1501.75   301.1 1487.43   306.61483.991
   311.9 1483.03   327.21484.072   350.8 1487.92   398.5 1488.69   430.9 1492.42
   444.3 1495.08   492.4 1514.53   533.7 1529.38   544.5 1534.84   555.3 1537.95
     566 1544.95     583 1552.98     604 1560.91   622.6 1566.13   631.1 1566.92
   641.9 1570.21   666.9 1574.93   684.9 1580.03   708.5 1581.35   720.8 1586.05
#Mann= 3 ,-1,0
       0      .1       0   306.6    .045       0   327.2      .1       0
Bank Sta=306.6,327.2
XS Rating Curve= 0 ,0
Exp/Cntr(USF)=0,0
Exp/Cntr=0.3,0.1

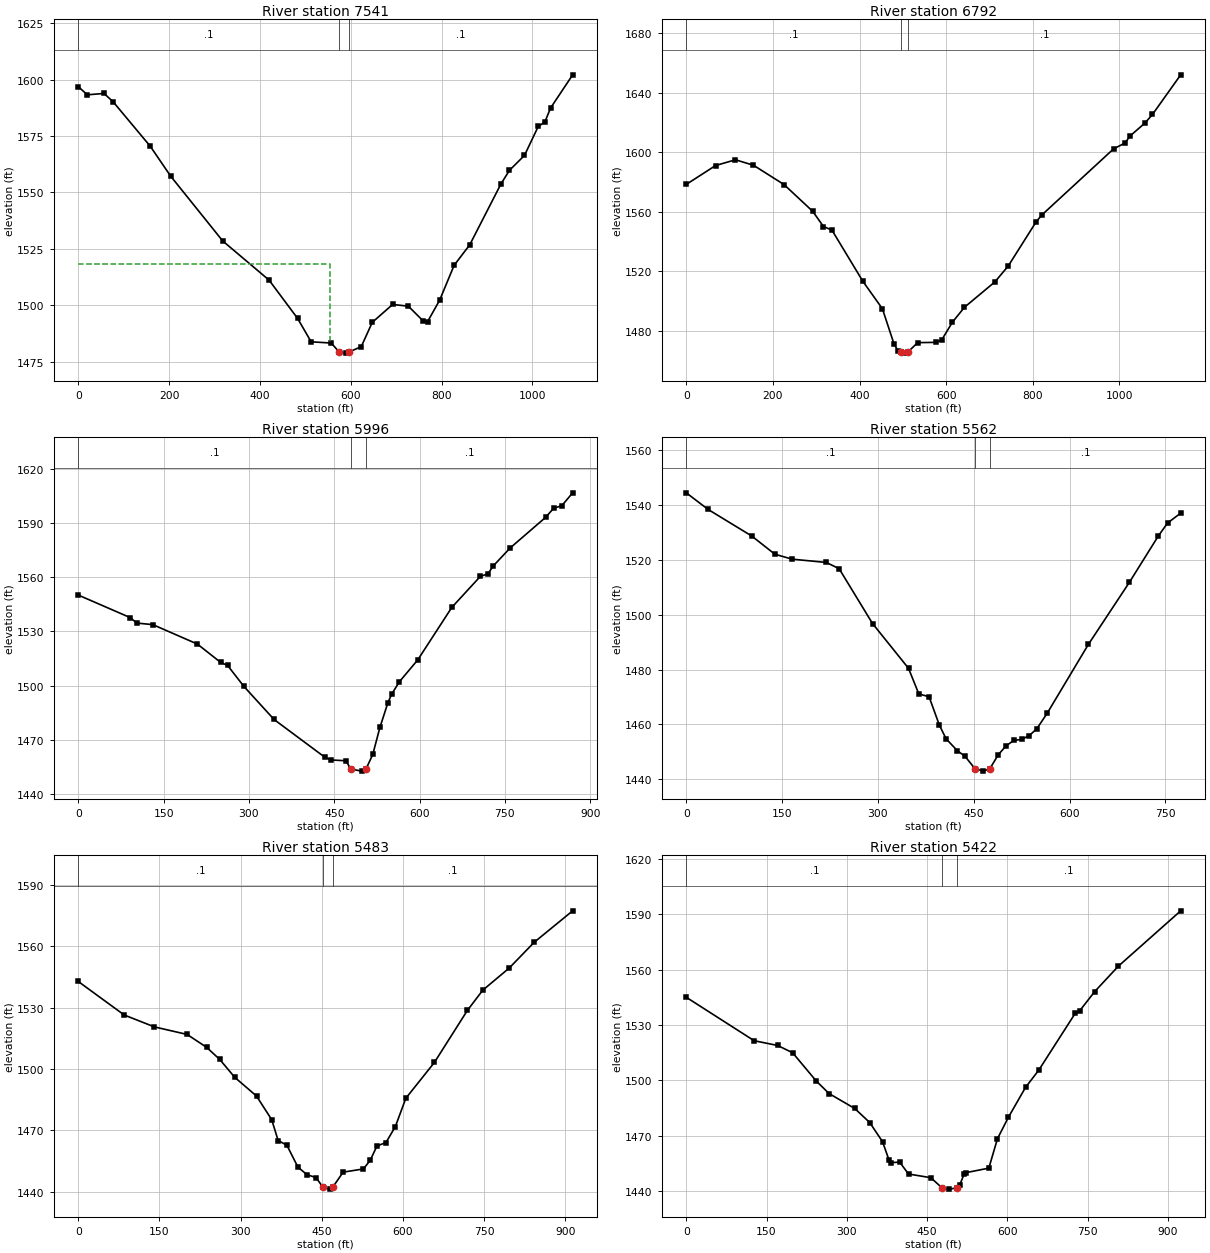
Type RM Length L Ch R = 1 ,7541    ,745.5,748.9,738.6
XS GIS Cut Line= 6
2150824.56243509669719.8121965832151069.80931993669671.332962841
2151177.35930167669639.9445741772151261.26858267669592.751099005
2151323.37672618669544.1783615052151637.66612384669090.918769345
#Sta/Elev= 30
       0 1596.92      20 1593.29    56.7  1593.9    76.8 1590.19   158.6 1570.47
   203.5 1557.23   318.1  1528.5   420.3 1511.12   482.9 1494.19   512.8  1483.8
   557.1 1483.25   574.7 1479.24   589.2 1478.78   595.2 1479.18   623.2 1481.66
   647.4 1492.42   692.3 1500.36   726.8 1499.59   759.5 1493.05   769.3 1492.77
   795.8 1502.26   827.7 1517.73   861.9 1526.74   930.8  1553.8   949.5 1559.81
   982.6 1566.43  1012.9 1579.26  1027.5 1581.24    1040 1587.43  1088.7 1602.15
#Mann= 3 ,-1,0
       0      .1       0   574.7    .045       0   595.2      .1       0
#XS Ineff= 2 , 0
          554.71 1518.21
Permanent Ineff=
       F       F
Bank Sta=574.7,595.2
XS Rating Curve= 0 ,0
Exp/Cntr(USF)=0,0
Exp/Cntr=0.3,0.1

Type RM Length L Ch R = 1 ,6792    ,775.4,795.6,801.7
XS GIS Cut Line= 6
2151193.51707776670621.8937257532151296.02441867670258.338350505
2151331.26680225670086.9239951672151415.25777601670036.750867173
2151527.87270826 669988.243746342151873.94878776669862.510073915
#Sta/Elev= 30
       0 1578.36    67.6 1591.03   113.5  1594.9   155.1 1591.24   225.7 1578.25
     292 1560.25   316.7 1550.08   336.3 1547.66   407.7 1513.27   452.8 1494.84
   479.8 1471.04   489.4 1466.35   495.31465.969   505.7 1465.04  512.441465.994
   534.2 1472.08   577.1 1472.28   589.7  1473.9   614.4 1485.79   642.2 1495.83
   712.6 1512.91   743.1 1523.47     808 1553.34   820.9 1557.82   986.7 1602.28
  1013.1 1606.16  1024.2 1610.79    1059 1619.59  1076.4 1625.36  1141.5 1651.96
#Mann= 3 ,-1,0
       0      .1       0   495.3    .045       0  512.44      .1       0
Bank Sta=495.3,512.44
XS Rating Curve= 0 ,0
Exp/Cntr(USF)=0,0
Exp/Cntr=0.3,0.1

Type RM Length L Ch R = 1 ,5996    ,421,434.4,436.3
XS GIS Cut Line= 4
2151407.18430135670573.8453457152151833.24527901 670662.54136379
2151921.67591562670612.8635669052152200.20216118670431.341190491
#Sta/Elev= 30
       0 1550.16    90.9 1537.72   103.2 1534.63   131.1 1533.77   209.4    1523
   250.2 1512.87   262.5 1511.17   291.1 1499.56   344.2 1481.21   433.1 1460.37
   444.2 1458.79   470.7 1458.34  478.86 1453.78   498.2  1452.6   505.9 1453.84
   517.7 1461.85   530.3 1476.85   544.4 1490.58   550.7  1495.1   564.2 1502.01
   596.9 1514.29   656.7 1543.34   706.7 1560.47   720.3 1561.96     729 1566.12
   759.2 1576.24   821.5  1593.2   835.6 1598.24     850 1599.68   869.1  1606.8
#Mann= 3 ,-1,0
       0      .1       0  478.86    .045       0   505.9      .1       0
Bank Sta=478.86,505.9
XS Rating Curve= 0 ,0
Exp/Cntr(USF)=0,0
Exp/Cntr=0.3,0.1

Type RM Length L Ch R = 1 ,5562    ,81.3,78.4,75.8
XS GIS Cut Line= 2
2151502.15980908 671092.74447985 2152272.0212449 671014.70010749
#Sta/Elev= 30
       0 1544.51    34.2 1538.44   102.5 1528.74   138.7  1522.1   165.7  1520.3
   219.1  1519.1   239.2 1516.83   291.5 1496.81   347.8 1480.47   363.9 1471.13
     380 1470.09     396 1459.78   406.6 1454.76   424.2 1450.41   436.2 1448.37
   451.7 1443.88     465 1442.95  475.13 1443.86   488.5 1448.99   500.6  1452.2
   512.6 1454.15   524.7 1454.52   536.8 1455.93   548.6 1458.41   564.9 1464.09
   629.3 1489.19   693.6 1511.89   738.8 1528.77   753.4 1533.52   773.8  1537.1
#Mann= 3 ,-1,0
       0      .1       0   451.7    .045       0  475.13      .1       0
Bank Sta=451.7,475.13
XS Rating Curve= 0 ,0
Exp/Cntr(USF)=0,0
Exp/Cntr=0.3,0.1

Type RM Length L Ch R = 1 ,5483    ,61.4,61.2,61.1
XS GIS Cut Line= 4
2151519.44881759671164.8554828382151911.21846725671142.388406155
2152083.93411925671091.8374836172152419.53607721671152.217752204
#Sta/Elev= 30
       0 1542.81    84.9 1526.41   140.6 1520.59   201.1 1516.89   237.1 1510.59
   261.2 1504.71   289.2 1495.87   329.3 1486.75   357.3 1475.21   369.3 1464.98
   385.4 1462.67   405.9 1451.92   422.6 1448.27   439.3 1446.82   451.8 1442.22
   464.3 1441.19   470.21442.132   489.3  1449.5   526.8 1451.06   539.4  1455.3
   551.8 1462.29   568.5    1464   585.9 1471.84   605.1 1485.63     658 1503.21
   718.9 1528.66   747.4 1538.57   796.2 1549.39   842.4 1562.02   913.4 1577.39
#Mann= 3 ,-1,0
       0      .1       0   451.8    .045       0   470.2      .1       0
Bank Sta=451.8,470.2
XS Rating Curve= 0 ,0
Exp/Cntr(USF)=0,0
Exp/Cntr=0.3,0.1

Type RM Length L Ch R = 1 ,5422    ,274.2,301.1,320.2
XS GIS Cut Line= 4
2151505.40689466671202.7686747412151908.41008267671206.981251619
2152065.67961945 671160.642905962152419.53607721671208.385443912
#Sta/Elev= 30
       0 1545.06   126.8 1521.53   170.8 1518.94   198.8 1514.98   242.8 1499.72
   266.8 1492.89   314.8  1484.8   342.8 1477.19   366.8 1466.78   378.8 1456.91
   382.8 1455.44   398.8 1455.74   415.3 1449.28     457 1447.29   478.4 1441.67
   490.4 1441.09   505.41441.702   511.2 1443.47   519.5 1449.42   522.6 1450.02
   565.4 1452.46   581.6 1468.44   601.9 1479.98   634.1 1496.27   658.6  1505.5
   726.9 1536.39     735 1537.65   763.2 1548.13   807.6 1561.95     924 1591.92
#Mann= 3 ,-1,0
       0      .1       0   478.4    .045       0   505.4      .1       0
Bank Sta=478.4,505.4
XS Rating Curve= 0 ,0
Exp/Cntr(USF)=0,0
Exp/Cntr=0.3,0.1