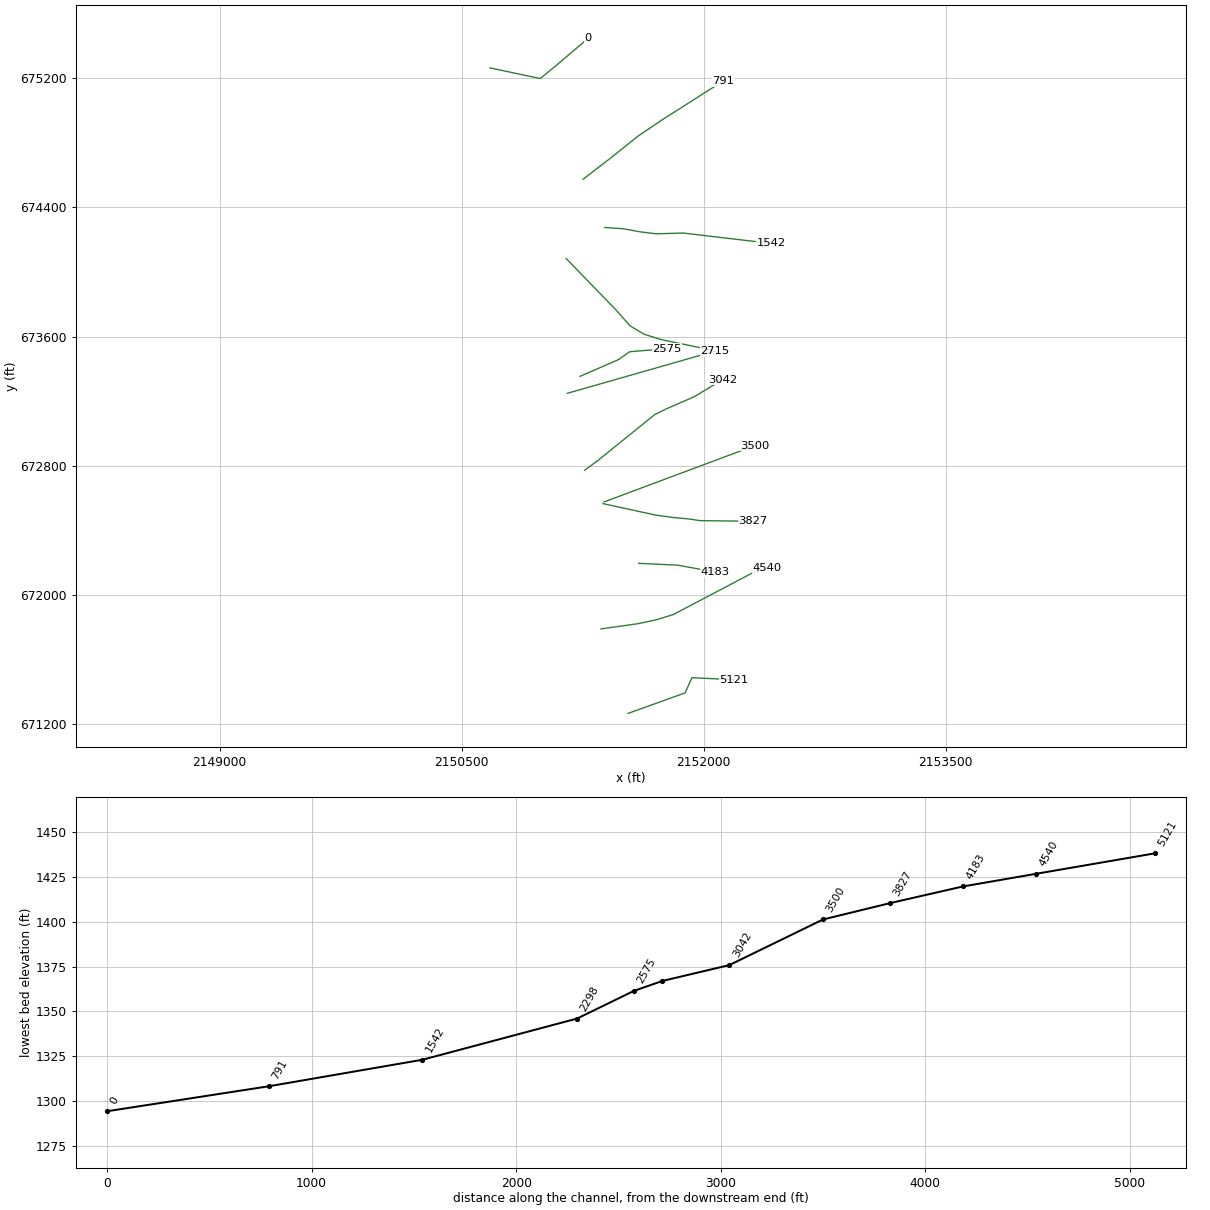
HEC-RAS study WHITECMPFK.prj: WHITECMPFK

--- WHITECMPFK.g01 (geometry) --- (continued)

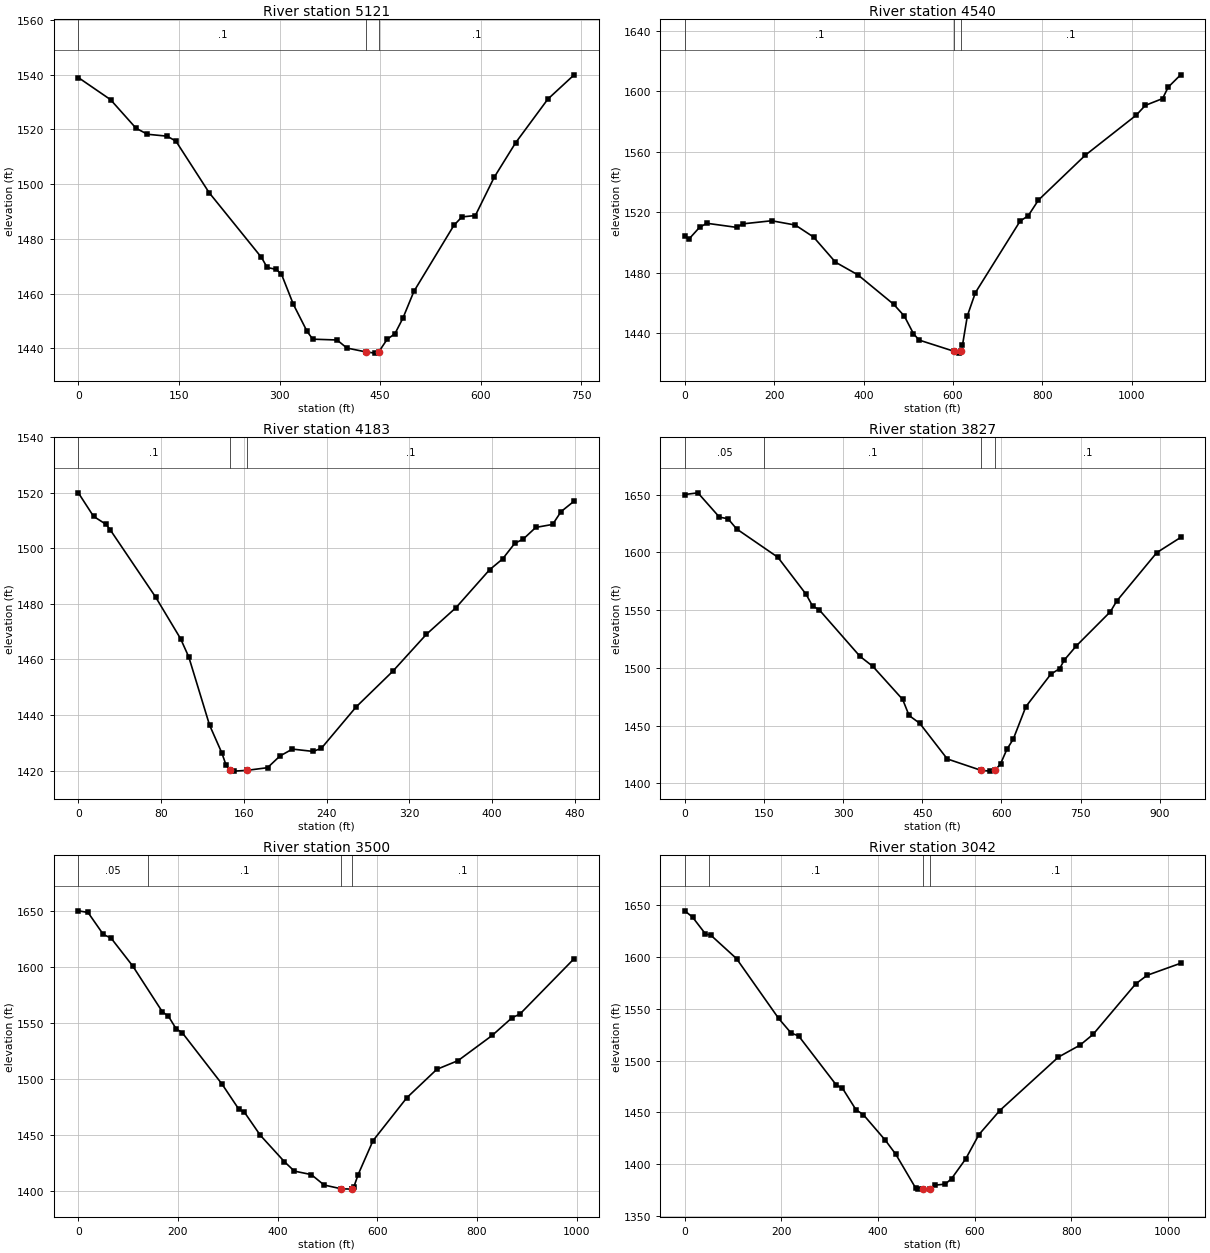
Type RM Length L Ch R = 1 ,5121    ,591.2,581.5,569.6
XS GIS Cut Line= 4
2151531.26110047671264.7066562362151884.44495504671391.694109567
2151926.77410615671485.6119135932152187.36294268671473.706839843
#Sta/Elev= 30
       0 1538.96      48 1530.89      86 1520.45     103 1518.24   132.4 1517.54
   145.5 1515.72   194.9 1496.93     273 1473.23   281.5 1469.57     295 1468.84
   302.8 1467.13   320.6 1456.07     341  1446.2   349.5 1443.35   385.7 1443.05
   400.4 1440.11   429.6 1438.65   442.7 1438.25  447.72 1438.66   460.3 1443.26
     472 1445.35   483.9 1451.03   500.3 1460.82   559.8 1484.91   571.8 1488.03
   591.9 1488.54   619.9 1502.47   651.9 1515.12     700 1531.09   739.2 1539.96
#Mann= 3 ,-1,0
       0      .1       0   429.6    .045       0  447.72      .1       0
Bank Sta=429.6,447.72
XS Rating Curve= 0 ,0
Exp/Cntr(USF)=0,0
Exp/Cntr=0.3,0.1

Type RM Length L Ch R = 1 ,4540    ,359.7,356.2,342.7
XS GIS Cut Line= 6
    2151363.4941671788.2181647572151588.22494976671819.719086006
2151702.67419593 671843.721662672151811.91774385671877.388262004
2152300.10574384672134.1308587492152394.46611942672165.937881753
#Sta/Elev= 30
       0 1504.38     8.8 1502.11    32.9 1509.98    49.1 1512.72   115.8 1510.01
   129.7 1512.33   194.5 1514.38   247.3 1511.54   288.2 1503.59   337.2 1486.97
   387.3  1478.6   467.4 1459.12   491.2 1451.35   511.7 1439.68   524.2 1435.47
   601.8  1428.1   612.5 1426.82  617.821428.103   621.3 1431.97   632.3 1451.51
   650.2 1466.79   750.3 1514.14   768.5  1517.7   791.3 1528.05   896.1 1557.72
    1010 1584.19  1030.6 1590.71  1069.1 1595.19  1081.7 1602.76  1109.5 1610.91
#Mann= 3 ,-1,0
       0      .1       0   601.8    .045       0  617.82      .1       0
Bank Sta=601.8,617.82
XS Rating Curve= 0 ,0
Exp/Cntr(USF)=0,0
Exp/Cntr=0.3,0.1

Type RM Length L Ch R = 1 ,4183    ,352.1,356.6,354.2
XS GIS Cut Line= 3
2151597.49811117672194.4715782392151839.35481939672183.063242946
2152072.65527614672140.281985595
#Sta/Elev= 30
       0 1520.03    14.7 1511.56    26.7 1508.69    30.7 1506.78    74.8 1482.43
    98.8 1467.51   106.8 1460.87   126.8 1436.41   138.8 1426.26   142.8 1421.94
  146.64 1420.09   150.8 1419.78   163.21420.065   182.9 1421.02   194.9 1425.22
   206.9 1427.72   226.9 1426.88   234.9 1427.99   268.5 1442.89     304 1455.76
   336.5 1469.08     365 1478.64   397.5  1492.3   410.1  1496.2   421.9 1501.84
     430 1503.34   442.2 1507.57   458.5 1508.65   466.6 1513.25   479.3 1517.05
#Mann= 3 ,-1,0
       0      .1       0  146.64    .045       0   163.2      .1       0
Bank Sta=146.64,163.2
XS Rating Curve= 0 ,0
Exp/Cntr(USF)=0,0
Exp/Cntr=0.3,0.1

Type RM Length L Ch R = 1 ,3827    ,313.8,326.6,331.4
XS GIS Cut Line= 6
  2151375.828721672564.5082788322151699.59939893672493.956254587
2151805.77405535672478.9205235092151915.13922869672468.599246669
2151974.70975025672459.1483981572152305.26601522672455.164695866
#Sta/Elev= 30
       0  1650.2    24.8 1651.67    65.6 1630.59    81.9 1629.21    98.2 1620.37
   176.3 1595.83   229.8 1563.74   242.1 1553.55   254.3 1550.47     332 1509.89
   356.2 1501.28   412.8 1472.59   424.9 1458.69   445.1 1451.91   497.3 1421.02
   561.7 1411.07   577.9 1410.46  587.56 1411.06   598.2 1416.76   610.3 1429.41
   622.3 1438.18   646.3 1466.43   693.3 1494.37   710.3 1499.39   718.9 1506.71
   741.9 1519.07   806.3 1548.62   818.3 1557.85   894.3 1599.87   939.4 1612.99
#Mann= 4 ,-1,0
       0     .05       0  150.01      .1       0   561.7    .045       0
  587.56      .1       0
Bank Sta=561.7,587.56
XS Rating Curve= 0 ,0
Exp/Cntr(USF)=0,0
Exp/Cntr=0.3,0.1

Type RM Length L Ch R = 1 ,3500    ,443.7,458.4,443.2
XS GIS Cut Line= 2
2151382.02519608672574.8334309552152314.37124609672923.081263862
#Sta/Elev= 30
       0 1649.98    19.4 1648.53    50.1  1628.9    65.7 1625.61   109.2 1600.69
   168.8 1559.69   180.7 1555.91   196.2 1544.67   208.7 1541.02   288.4 1495.21
   322.5 1472.53     333 1470.31   365.2 1449.53   413.8  1425.8   433.6 1417.46
   467.7 1414.34   493.3 1405.03   527.5 1401.68   548.8 1401.36  550.031401.879
   553.1  1403.4   561.7 1414.37   591.5 1444.63   659.4    1483   719.6 1508.38
   762.3 1516.18   830.7 1538.65   870.8 1554.54   886.2 1557.64   995.3 1607.26
#Mann= 4 ,-1,0
       0     .05       0     140      .1       0   527.5    .045       0
  550.03      .1       0
Bank Sta=527.5,550.03
XS Rating Curve= 0 ,0
Exp/Cntr(USF)=0,0
Exp/Cntr=0.3,0.1

Type RM Length L Ch R = 1 ,3042    ,328.9,326.7,319.7
XS GIS Cut Line= 6
2151262.02612709672771.7034025042151341.59027243672829.826973915
2151697.39238234673117.1794175952151768.91487709673152.029085428
2151940.96833876673226.7517050062152114.66877876673331.811862335
#Sta/Elev= 30
       0 1644.58    16.1 1638.45    42.7 1622.31    54.1 1620.96     107 1598.45
   194.3 1540.63   220.1 1526.53   235.5 1523.84   313.6 1476.34   326.3  1473.3
   354.1 1452.62   369.6 1447.71   415.1 1423.02   436.6 1409.55   477.6 1377.04
   482.7 1375.88     493 1376.11  507.18 1376.11   518.5 1379.78     539 1380.68
   552.2 1386.11   581.2 1404.97   608.8  1428.6   651.9 1451.79     773 1503.32
   817.8 1514.88   844.8 1525.22   933.1 1574.01   956.8 1582.34  1026.1 1593.95
#Mann= 4 ,-1,0
       0     .05       0      50      .1       0     493    .045       0
  507.18      .1       0
Bank Sta=493,507.18
XS Rating Curve= 0 ,0
Exp/Cntr(USF)=0,0
Exp/Cntr=0.3,0.1

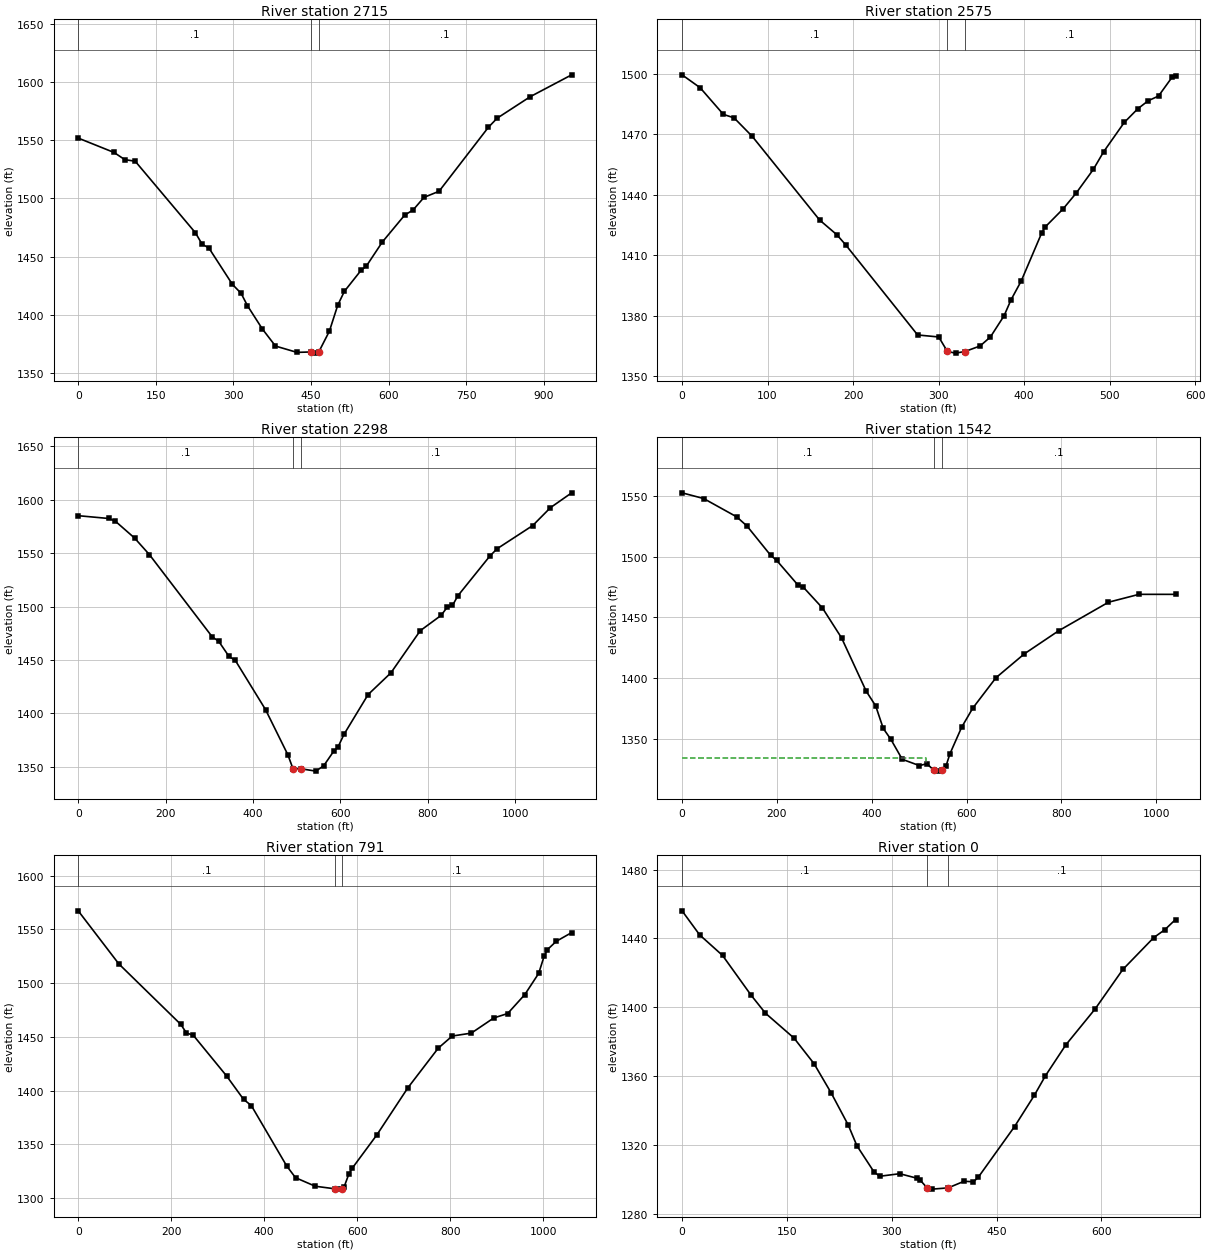
Type RM Length L Ch R = 1 ,2715    ,135,140.4,144.1
XS GIS Cut Line= 2
2151153.51274309673247.7194288172152070.64828589673509.651548853
#Sta/Elev= 30
       0 1551.93    69.3 1539.56    90.1 1533.38   110.1 1532.06   226.6  1470.5
   239.5 1460.66   252.4 1457.56   298.1 1426.12   314.8  1418.5   327.2 1407.78
     356 1387.77   381.3 1373.13   422.9 1367.69   449.61368.058   456.9 1367.05
  465.061368.118   485.5 1385.92   501.6 1408.19   514.4 1420.13   546.9 1438.35
   556.7 1441.72   587.9 1462.61   630.9 1485.65   647.3 1490.14   668.4 1500.97
   697.5 1506.21   792.9 1561.25   809.8 1569.04   873.8 1587.54   953.8 1606.32
#Mann= 3 ,-1,0
       0      .1       0   449.6    .045       0  465.06      .1       0
Bank Sta=449.6,465.06
XS Rating Curve= 0 ,0
Exp/Cntr(USF)=0,0
Exp/Cntr=0.3,0.1

Type RM Length L Ch R = 1 ,2575    ,296,276.7,254.6
XS GIS Cut Line= 4
2151232.78403363673352.9532550812151472.73987428673457.281881451
2151540.98417607673505.6872081452151772.00296576673524.682086409
#Sta/Elev= 30
       0  1499.4    21.1 1493.02    48.3 1479.79    60.8 1478.07    82.2 1468.83
   160.8 1427.46   181.1  1420.1   191.3 1415.15   275.5 1370.45   300.2 1369.46
   310.3 1362.26   319.8 1361.45   330.7 1362.23   348.5 1364.99   360.6 1369.44
   376.6 1379.98   384.6 1387.77   396.7 1397.25   420.8 1421.22   424.8 1424.03
   445.6 1432.93   460.9 1440.76     481 1452.53     493 1461.24   517.1 1475.77
   533.1 1482.62   545.2 1486.56   557.2 1488.88   573.3 1498.34   577.1 1498.77
#Mann= 3 ,-1,0
       0      .1       0   310.3    .045       0   330.7      .1       0
Bank Sta=310.3,330.7
XS Rating Curve= 0 ,0
Exp/Cntr(USF)=0,0
Exp/Cntr=0.3,0.1

Type RM Length L Ch R = 1 ,2298    ,737.5,756.4,758.3
XS GIS Cut Line= 6
2151147.70056833674082.9097695952151462.08609442673758.339880675
2151542.15089493673666.900102928  2151628.702231673614.843120426
2151733.74434376673581.5429901782152071.34078142673511.065440834
#Sta/Elev= 30
       0 1585.15    69.5 1582.54    84.6 1580.14   128.9 1564.27   162.9 1548.75
   307.1 1471.58   321.3 1467.75   345.2 1453.41   359.7 1449.63   428.8 1403.64
   480.1  1361.2   491.5 1348.41   509.51348.284   543.9 1346.05   561.9 1351.02
   584.9 1364.71   594.5 1368.42   608.5 1380.52   663.6 1417.71   715.9 1438.08
     783  1477.5   830.6 1491.79   844.5 1499.32   856.8  1501.1   869.1 1510.19
   942.6 1547.49     959 1554.23  1040.5 1575.94  1081.1 1592.69  1129.6 1606.55
#Mann= 3 ,-1,0
       0      .1       0   491.5    .045       0   509.5      .1       0
Bank Sta=491.5,509.5
XS Rating Curve= 0 ,0
Exp/Cntr(USF)=0,0
Exp/Cntr=0.3,0.1

Type RM Length L Ch R = 1 ,1542    ,737.6,750.3,756.4
XS GIS Cut Line= 6
2151386.66203268 674275.48648417  2151501.600123674267.884137169
2151606.34072718674248.5213150082151705.84118435674236.501653999
2151872.80049609 674241.187340172152420.59303567 674176.46306017
#Sta/Elev= 30
       0 1553.02    45.6 1548.29   115.2 1533.17   136.9 1525.59     187  1501.3
   199.2 1497.31   244.3 1476.85   255.8 1475.01   296.1 1457.83   336.3 1433.18
   388.3 1389.11   408.3 1376.95   424.3  1358.3   440.3 1349.32   464.3 1332.82
   500.4 1327.63   516.5 1329.16  531.19 1323.61   540.7 1323.05   548.7 1323.59
   556.8  1327.5   564.8  1337.3   589.6 1359.32   613.1 1375.13   661.9  1400.2
   721.9 1419.99   794.4 1439.09   899.2 1462.62   963.6 1469.14  1040.6 1469.12
#Mann= 3 ,-1,0
       0      .1       0  531.19    .045       0   548.7      .1       0
#XS Ineff= 2 , 0
          514.47 1334.16
Permanent Ineff=
       F       F
Bank Sta=531.19,548.7
XS Rating Curve= 0 ,0
Exp/Cntr(USF)=0,0
Exp/Cntr=0.3,0.1

Type RM Length L Ch R = 1 ,791     ,791.2,791.2,791.2
XS GIS Cut Line= 6
2151252.32142209    674574.60334 2151430.4293336674711.789417341
2151594.00315343674842.7543785132151739.11441176674940.569471583
2152036.98061392675130.4496692572152120.68681134675182.389854088
#Sta/Elev= 30
       0 1567.25    87.3 1517.89   220.6 1461.54   232.7  1453.6   247.5  1451.4
   318.9 1413.67   355.6 1391.78   372.2 1386.07   448.2 1329.89   467.3 1318.89
   509.7 1310.96  551.29 1308.59   555.8 1308.26   567.2 1308.58   572.1 1310.67
   581.8 1322.15     589 1327.58   642.4 1358.87     709 1402.63   774.3  1439.5
   804.3 1450.73   845.3 1453.44   893.8 1467.61   923.4 1471.64   960.3 1489.28
   990.2 1509.05  1001.8 1524.89  1008.7 1531.03  1027.9 1538.86  1061.1    1547
#Mann= 3 ,-1,0
       0      .1       0  551.29    .045       0   567.2      .1       0
Bank Sta=551.29,567.2
XS Rating Curve= 0 ,0
Exp/Cntr(USF)=0,0
Exp/Cntr=0.3,0.1

Type RM Length L Ch R = 1 ,0       ,254.6,242.3,232
XS GIS Cut Line= 4
2150675.49997512 675264.535811442150986.76020207675198.615048843
2151082.24343489675276.9646695552151283.85303606675447.707809714
#Sta/Elev= 30
       0 1456.02    25.2 1442.03    57.9  1430.1    98.8 1406.97   119.3 1396.53
   160.2 1382.05   188.8  1367.2   213.3  1350.2   237.8 1331.49   250.1 1319.53
   274.6 1304.29   282.8 1301.79   311.4 1303.27   335.5  1300.7   340.7  1299.5
  350.61 1295.01   357.9 1294.31   380.7 1295.04   403.4 1298.88   416.8 1298.58
   423.5 1301.08   475.7  1330.7   503.9  1348.8   519.8 1360.16     549 1378.14
     591 1399.05   630.5 1421.93   674.8 1440.48   690.6 1445.04   705.9 1450.97
#Mann= 3 ,-1,0
       0      .1       0  350.61    .045       0   380.7      .1       0
Bank Sta=350.61,380.7
XS Rating Curve= 0 ,0
Exp/Cntr=0.3,0.1
LCMann Table=0

Chan Stop Cuts=-1
Use User Specified Reach Order=0
Composite Channel Slope=5